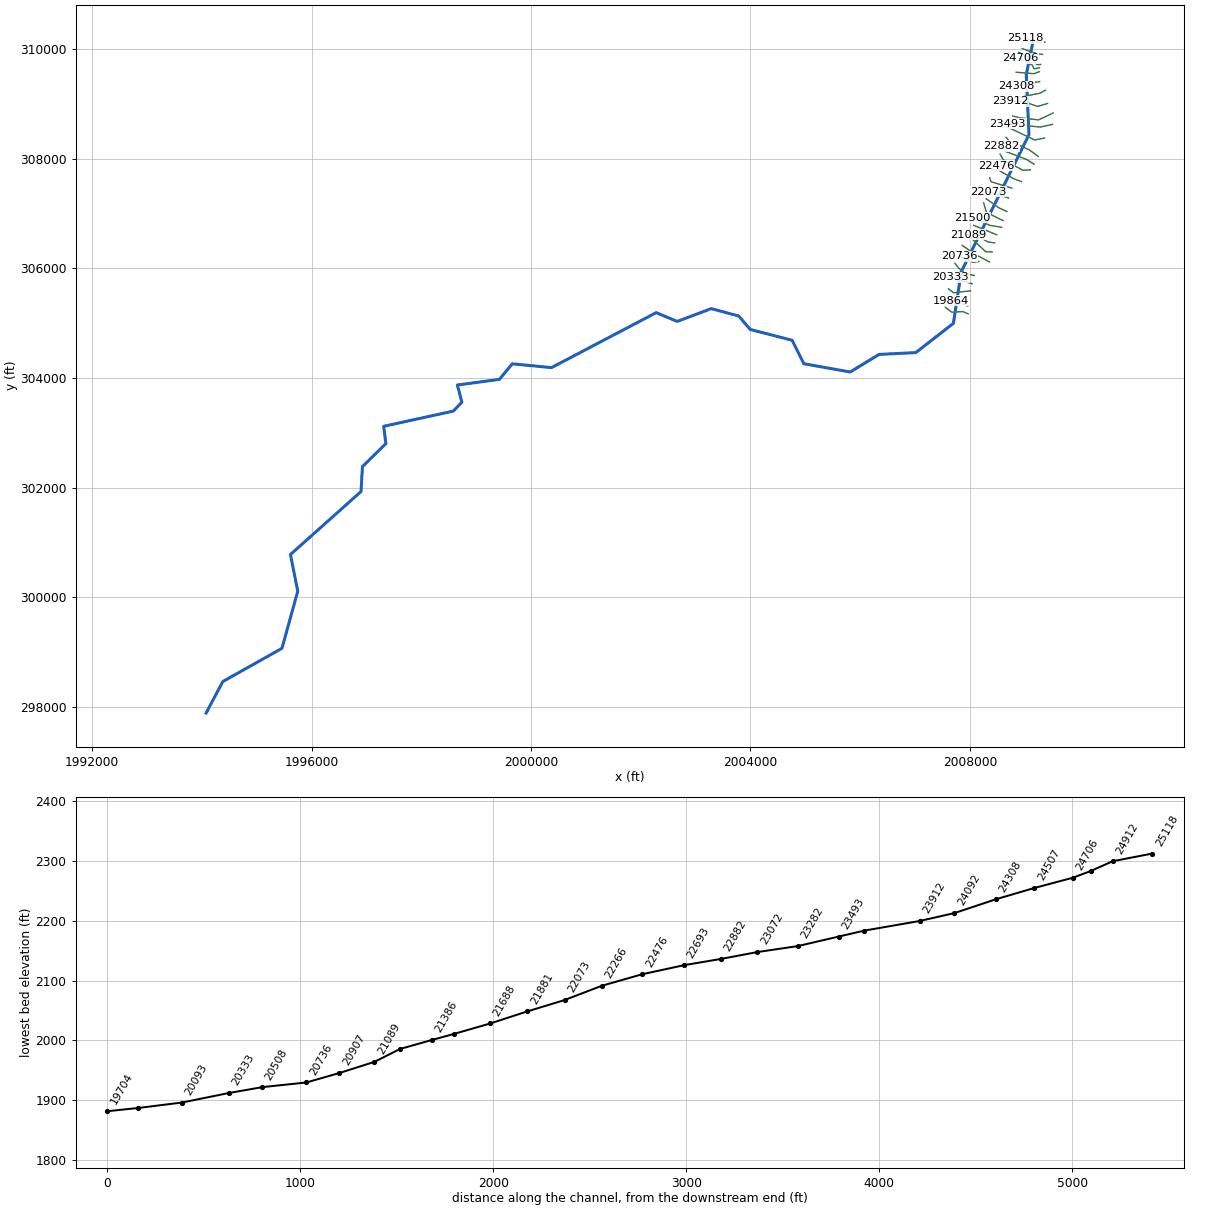
--- MEADOWCK_A.prj (project) ---

Proj Title=MEADOWCK_A
Current Plan=p01
Default Exp/Contr=0,0
English Units
Geom File=g01
Flow File=f01
Plan File=p01
BEGIN DESCRIPTION:
Stream Name: Meadow Creek
Flood Zone: Approximate
Summers County, West Virginia
HEC-RAS Version: 5.0.7
Hydrology Method:
regression
Model Notes:
KWSELtie in with Meadow Creek detailed model
END DESCRIPTION:
DSS File=dss
DSS Export Rating Curves= 0
DSS Export Rating Curve Sorted= 0
DSS Export Volume Flow Curves= 0
DXF OffsetX= 0
DXF OffsetY= 0
DXF ScaleX= 0
DXF ScaleY= 0

--- MEADOWCK_A.p01 (plan) ---

Plan Title=Floodplain
Program Version=5.07
Short Identifier=Floodplain
Geom File=g01
Flow File=f01
Subcritical Flow
K Sum by GR= 0
Std Step Tol= 0.01
Critical Tol= 0.01
Num of Std Step Trials= 20
Max Error Tol= 0.3
Flow Tol Ratio= 0.001
Split Flow NTrial= 30
Split Flow Tol= 0.02
Split Flow Ratio= 0.02
Log Output Level= 0
Friction Slope Method= 1
Unsteady Friction Slope Method= 2
Unsteady Bridges Friction Slope Method= 1
Parabolic Critical Depth
Global Vel Dist= 0 , 0 , 0
Global Log Level= 0
CheckData=True
Encroach Param=-1 ,0,0, 0
Computation Interval=0.1SEC
Output Interval=1MIN
Instantaneous Interval=Max Profile
Mapping Interval=1HOUR
Computation Time Step Use Courant=        0
Computation Time Step Use Time Series=    0
Computation Time Step Count To Double=0
Computation Time Step Max Doubling=0
Computation Time Step Max Halving=0
Computation Time Step Residence Courant=0
Run HTab= 0
Run UNet= 0
Run Sediment= 0
Run PostProcess= 0
Run WQNet= 0
Run RASMapper= 0
UNET Theta= 0
UNET Theta Warmup= 0
UNET ZTol= 0
UNET ZSATol= 0
UNET MxIter= 0
UNET Max Iter WO Improvement= 0
UNET MaxInSteps= 0
UNET DtIC= 0
UNET DtMin= 0
UNET MaxCRTS= 0
UNET WFStab= 0
UNET SFStab= 0
UNET WFX= 1
UNET SFX= 1
UNET 1D Methodology=Finite Difference
UNET DSS MLevel= 1
UNET Pardiso=0
UNET DZMax Abort= 0
UNET Use Existing IB Tables= 0
UNET Froude Reduction=False
UNET Froude Limit= 0
UNET Froude Power= 0
UNET D1 Cores= 0
UNET D2 Coriolis=0
UNET D2 Cores= 0
UNET D2 Theta= 1
UNET D2 Theta Warmup= 1
UNET D2 Z Tol= 0.01
UNET D2 Volume Tol= 0.01
UNET D2 Max Iterations= 20
UNET D2 Equation= 0
UNET D2 RampUpFraction=0.1
UNET D2 TimeSlices= 1
UNET D2 BCVolumeCheck=0
UNET D1D2 MaxIter= 0
UNET D1D2 ZTol=0.01
UNET D1D2 QTol=0.1
UNET D1D2 MinQTol=1
DSS File=dss
Write IC File= 0
Write IC File at Fixed DateTime=0
Write IC File at Sim End=0
Echo Input=False
Echo Parameters=False
Echo Output=False
Write Detailed= 0
HDF Write Warmup=0
HDF Write Time Slices=0
HDF Flush=0
HDF Face Node Velocities=0
HDF Compression= 1
HDF Chunk Size= 1
HDF Spatial Parts= 1
HDF Use Max Rows=0
HDF Fixed Rows= 1
Calibration Method= 0
Calibration Iterations= 20
Calibration Max Change=0.05
Calibration Tolerance=0.2
Calibration Maximum=1.5
Calibration Minimum=0.5
Calibration Optimization Method= 1
WQ AD Non Conservative
WQ ULTIMATE=-1
WQ Max Comp Step=1HOUR
WQ Output Interval=15MIN
WQ Output Selected Increments= 0
WQ Output face flow=0
WQ Output face velocity=0
WQ Output face area=0
WQ Output face dispersion=0
WQ Output cell volume=0
WQ Output cell surface area=0
WQ Output cell continuity=0
WQ Output cumulative cell continuity=0
WQ Output face conc=0
WQ Output face dconc_dx=0
WQ Output face courant=0
WQ Output face peclet=0
WQ Output face adv mass=0
WQ Output face disp mass=0
WQ Output cell mass=0
WQ Output cell source sink temp=0
WQ Output nsm pathways=0
WQ Output nsm derived pathways=0
WQ Output MaxMinRange=-1
WQ Daily Max Min Mean=-1
WQ Daily Range=0
WQ Daily Time=0
WQ Create Restart=0
WQ Fixed Restart=0
WQ System Summary=0
WQ Write To DSS=0
WQ Use Fixed Temperature=0
Sorting and Armoring Iterations= 10
XS Update Threshold= 0.02
Bed Roughness Predictor= 0
Hydraulics Update Threshold= 0.02
Energy Slope Method= 1
Volume Change Method= 1
Sediment Retention Method= 0
XS Weighting Method= 0
Number of US Weighted Cross Sections= 1
Number of DS Weighted Cross Sections= 1
Upstream XS Weight=0
Main XS Weight=1
Downstream XS Weight=0
Number of DS XS's Weighted with US Boundary= 1
Upstream Boundary Weight= 1
Weight of XSs Associated with US Boundary= 0
Number of US XS's Weighted with DS Boundary= 1
Downstream Boundary Weight= 0.5
Weight of XSs Associated with DS Boundary= 0.5
Percentile Method= 0
Sediment Output Level= 3
Mass or Volume Output= 0
Output Increment Type= 1
Profile and TS Output Increment= 1
XS Output Flag= 0
XS Output Increment= 10
Write Gradation File= 0
Read Gradation Hotstart= 0
Write HDF5 File= 1
Write Binary Output= 1
Write DSS Sediment File= 0
SV Curve= 0
Specific Gage Flag= 0

--- MEADOWCK_A.f01 (steady flow) ---

Flow Title=Flows
Program Version=5.07
Number of Profiles= 6
Profile Names=01pct,10pct,04pct,02pct,0_2pct,01plus
River Rch & RM=MEADOWCK_A,Main            ,25118
    1984    1100    1430    1698    2708    2935
River Rch & RM=MEADOWCK_A,Main            ,23282
    2654    1488    1923    2277    3602    3925
River Rch & RM=MEADOWCK_A,Main            ,16766
    3202    1809    2329    2752    4331    4736
River Rch & RM=MEADOWCK_A,Main            ,8803
    4180    2386    3057    3601    5625    6182
River Rch & RM=MEADOWCK_A,Main            ,0
    4358    2491    3190    3756    5860    6445
Boundary for River Rch & Prof#=MEADOWCK_A,Main            , 1
Up Type= 0
Dn Type= 1
Dn Known WS=1380.2
Boundary for River Rch & Prof#=MEADOWCK_A,Main            , 2
Up Type= 0
Dn Type= 1
Dn Known WS=1378.6
Boundary for River Rch & Prof#=MEADOWCK_A,Main            , 3
Up Type= 0
Dn Type= 1
Dn Known WS=1379.2
Boundary for River Rch & Prof#=MEADOWCK_A,Main            , 4
Up Type= 0
Dn Type= 1
Dn Known WS=1379.8
Boundary for River Rch & Prof#=MEADOWCK_A,Main            , 5
Up Type= 0
Dn Type= 1
Dn Known WS=1381.4
Boundary for River Rch & Prof#=MEADOWCK_A,Main            , 6
Up Type= 0
Dn Type= 1
Dn Known WS=1381.7
DSS Import GetInterval= 0
DSS Import GetPeak= 0
DSS Import FillOption= 0

--- MEADOWCK_A.g01 (geometry) ---

Geom Title=Geometry
Program Version=5.07

River Reach=MEADOWCK_A      ,Main
Reach XY= 30
      2009156.57310159.4749999122009028.14743145309530.757302642
     2009076.847308435.450999914 2007841.7523416305934.782315049
2007699.58999999304996.214999911     2007013.826304463.227999907
2006343.66522739304429.8305839032005817.64599999304109.061999916
     2004972.269304260.2599999172004760.46399999304687.342999913
2003994.83899999304885.259999905     2003786.506305130.051999916
2003284.55977484305264.9260782252002664.97799999 305031.09299991
2002281.50104583305191.504300957     2000372.848304189.136999915
1999658.32093484304258.2957153441999423.30703902303975.082952806
1998656.65805712303872.203251609 1998738.8311072303560.644314153
1998584.65399999303397.0359999111997312.95199999303119.258999916
     1997354.185302804.5889999111996926.19234762302384.408742453
1996900.62599999301930.0229999071995613.73399999300782.018999906
1995747.22080869300114.225240015     1995459.654299071.948999913
     1994381.095298466.4809999121994076.67040918297892.234839442

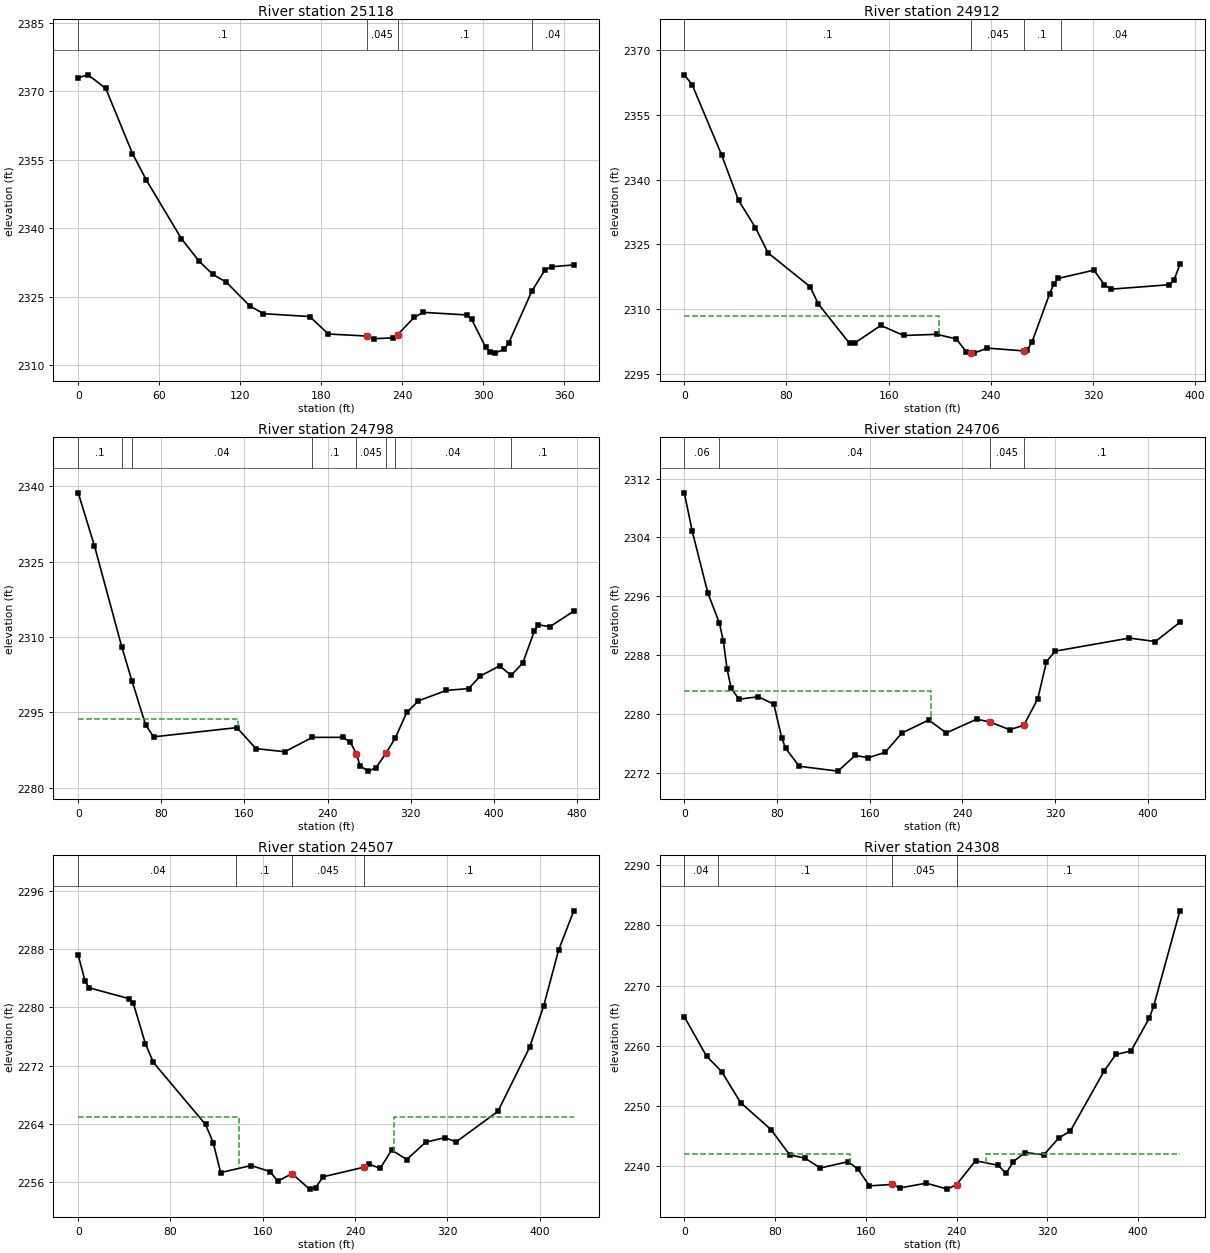
Type RM Length L Ch R = 1 ,25118   ,204.9,205.8,202.3
XS GIS Cut Line= 3
2009367.69029034310122.003354832  2009271.701662310114.715133126
2009012.33081554310192.361182702
#Sta/Elev= 30
       0 2372.96     7.3 2373.59    20.4 2370.61    40.2 2356.36    50.5 2350.52
    76.4 2337.72    89.5 2332.79    99.5 2329.92   109.8 2328.15   126.9 2323.02
   137.2 2321.28   171.5 2320.65   185.2 2316.83   213.8 2316.38   219.4 2315.81
   233.1 2315.98   236.5 2316.67   248.8 2320.46   255.5 2321.57   287.9    2321
   291.3 2320.06   301.7 2313.97     305 2312.81   308.4 2312.64   315.3 2313.45
   318.7 2314.77   335.8 2326.14   345.7 2330.89   350.6 2331.56     367 2331.96
#Mann= 4 ,-1 , 0
       0      .1       0   213.8    .045       0   236.5      .1       0
  336.26     .04       0
Bank Sta=213.8,236.5
XS Rating Curve= 0 ,0
Exp/Cntr=0.3,0.1

Type RM Length L Ch R = 1 ,24912   ,124.1,114.1,115.4
XS GIS Cut Line= 3
2009323.87984356309899.5767824152009219.78993901309911.088556747
2008952.45718651310005.115646002
#Sta/Elev= 30
       0 2364.29     6.1 2362.03    29.2 2345.74    42.5 2335.19    55.7 2328.88
    65.6 2323.02    98.6 2315.16     105 2311.14   129.5 2302.02   133.3 2302.09
   153.9 2306.19   171.9 2303.87   197.7 2304.14     213 2303.07   220.8  2300.1
   224.62299.911   226.9 2299.78   237.3 2300.94   265.92300.297   268.6 2300.57
   272.3 2302.35     286 2313.47   289.5 2315.91     293 2317.11   320.8 2319.02
   328.9 2315.65     334  2314.6   379.9 2315.64   383.4 2316.63   388.1 2320.33
#Mann= 4 ,-1 , 0
       0      .1       0   224.6    .045       0   265.9      .1       0
  294.72     .04       0
#XS Ineff= 2 , 0
          199.35 2308.48
Permanent Ineff=
       F       F
Bank Sta=224.6,265.9
XS Rating Curve= 0 ,0
Exp/Cntr=0.3,0.1

Type RM Length L Ch R = 1 ,24798   ,92,91.7,88.8
XS GIS Cut Line= 4
2009290.75166033309715.6119344562009218.20839647309712.183094708
 2009177.9689913309783.8305870292008893.94211031309936.234308095
#Sta/Elev= 30
       0 2338.69    15.6 2328.18    41.9 2308.08    51.8  2301.2    64.9 2292.52
    72.6 2290.13   152.8 2291.97   171.1 2287.79   198.8 2287.17   225.5 2290.03
   254.5 2290.03   261.8 2289.13   267.9 2286.75   271.2 2284.39   279.1 2283.31
   286.6 2283.97   296.3 2286.87   305.2 2289.88   316.3 2294.99   327.5 2297.29
   354.4 2299.38   375.9 2299.73   387.1 2302.23   405.7 2304.25   416.8 2302.38
     428 2304.82   439.2 2311.25   442.9 2312.42   454.1 2312.06   477.1 2315.14
#Mann= 8 ,-1 , 0
       0      .1       0    41.9     .06       0    51.8     .04       0
   225.5      .1       0   267.9    .045       0   296.3      .1       0
   305.2     .04       0   416.8      .1       0
#XS Ineff= 2 , 0
          153.43 2293.65     310         2288.66
Permanent Ineff=
       F       F
Bank Sta=267.9,296.3
XS Rating Curve= 0 ,0
Exp/Cntr(USF)=0,0
Exp/Cntr=0.5,0.3

Type RM Length L Ch R = 1 ,24706   ,192.2,199.5,208.5
XS GIS Cut Line= 4
 2009268.7073988309656.1607942672009171.62463088309635.435685649
2009133.30026625309708.4342202542008918.79089494309828.687701028
#Sta/Elev= 30
       0 2310.08     6.9 2304.83    20.3 2296.46    30.3 2292.34    33.7  2289.9
    36.9 2286.13    40.4 2283.49    47.1 2281.99    63.9 2282.32    77.3 2281.31
      84 2276.76    87.4 2275.31    99.2 2272.86   132.6  2272.2   147.5 2274.34
   158.6 2274.02   173.3 2274.76   187.8 2277.39   210.9 2279.16     226  2277.4
   252.3 2279.27   263.82278.885   280.7 2277.84   292.92278.432     305 2282.05
   312.5 2287.11     320 2288.53     384 2290.31   406.5 2289.84   427.6 2292.46
#Mann= 4 ,-1 , 0
       0     .06       0    30.3     .04       0   263.8    .045       0
   292.9      .1       0
#XS Ineff= 2 , 0
          213.28 2283.05
Permanent Ineff=
       F       F
Bank Sta=263.8,292.9
XS Rating Curve= 0 ,0
Exp/Cntr(USF)=0,0
Exp/Cntr=0.5,0.3

Type RM Length L Ch R = 1 ,24507   ,182.7,199,204.4
XS GIS Cut Line= 3
2009267.57426885309584.1118364612009166.74992716309547.707613296
2008845.40991803309574.025981086
#Sta/Elev= 30
       0 2287.18     5.9 2283.64     9.4 2282.69    44.3 2281.19    47.8 2280.58
    58.2 2275.04    65.2 2272.44   110.4 2263.93     117 2261.45   123.5 2257.33
   149.9  2258.3   166.3 2257.47   172.9 2256.16   185.4 2257.18   200.6 2255.06
   205.8 2255.28   212.4 2256.76   247.8 2258.07   252.4 2258.48   261.8 2257.91
   271.7 2260.43   284.8 2259.12   301.3 2261.51   317.8 2262.12   327.6 2261.54
   363.8 2265.73   391.3 2274.52   403.4 2280.14   416.5  2287.9   429.6 2293.25
#Mann= 4 ,-1 , 0
       0     .04       0   137.2      .1       0   185.4    .045       0
   247.8      .1       0
#XS Ineff= 2 , 0
             139    2265     274            2265
Permanent Ineff=
       F       F
Bank Sta=185.4,247.8
XS Rating Curve= 0 ,0
Exp/Cntr=0.3,0.1

Type RM Length L Ch R = 1 ,24308   ,213.2,215.5,217.5
XS GIS Cut Line= 2
2009271.38790468309403.428911767 2008842.4008565 309321.34082602
#Sta/Elev= 30
       0 2264.81    19.6 2258.28    32.9 2255.72    49.6 2250.57    76.4 2246.09
    92.9 2241.89   106.4 2241.34   119.8 2239.71   144.6 2240.76   153.2 2239.49
   163.2 2236.74   183.3 2236.98   189.9 2236.39   213.3 2237.19   231.8  2236.2
     240 2236.96   256.7 2240.91   276.8 2240.15   283.5  2238.8   290.1 2240.77
   300.2 2242.28   316.9  2241.9   330.2 2244.71   340.3 2245.86     370 2255.79
   380.3 2258.55   393.7 2259.13   409.8 2264.58   413.7 2266.59   436.8  2282.4
#Mann= 4 ,-1 , 0
       0     .04       0      30      .1       0   183.3    .045       0
     240      .1       0
#XS Ineff= 2 , 0
             146    2242     266            2242
Permanent Ineff=
       F       F
Bank Sta=183.3,240
XS Rating Curve= 0 ,0
Exp/Cntr=0.3,0.1

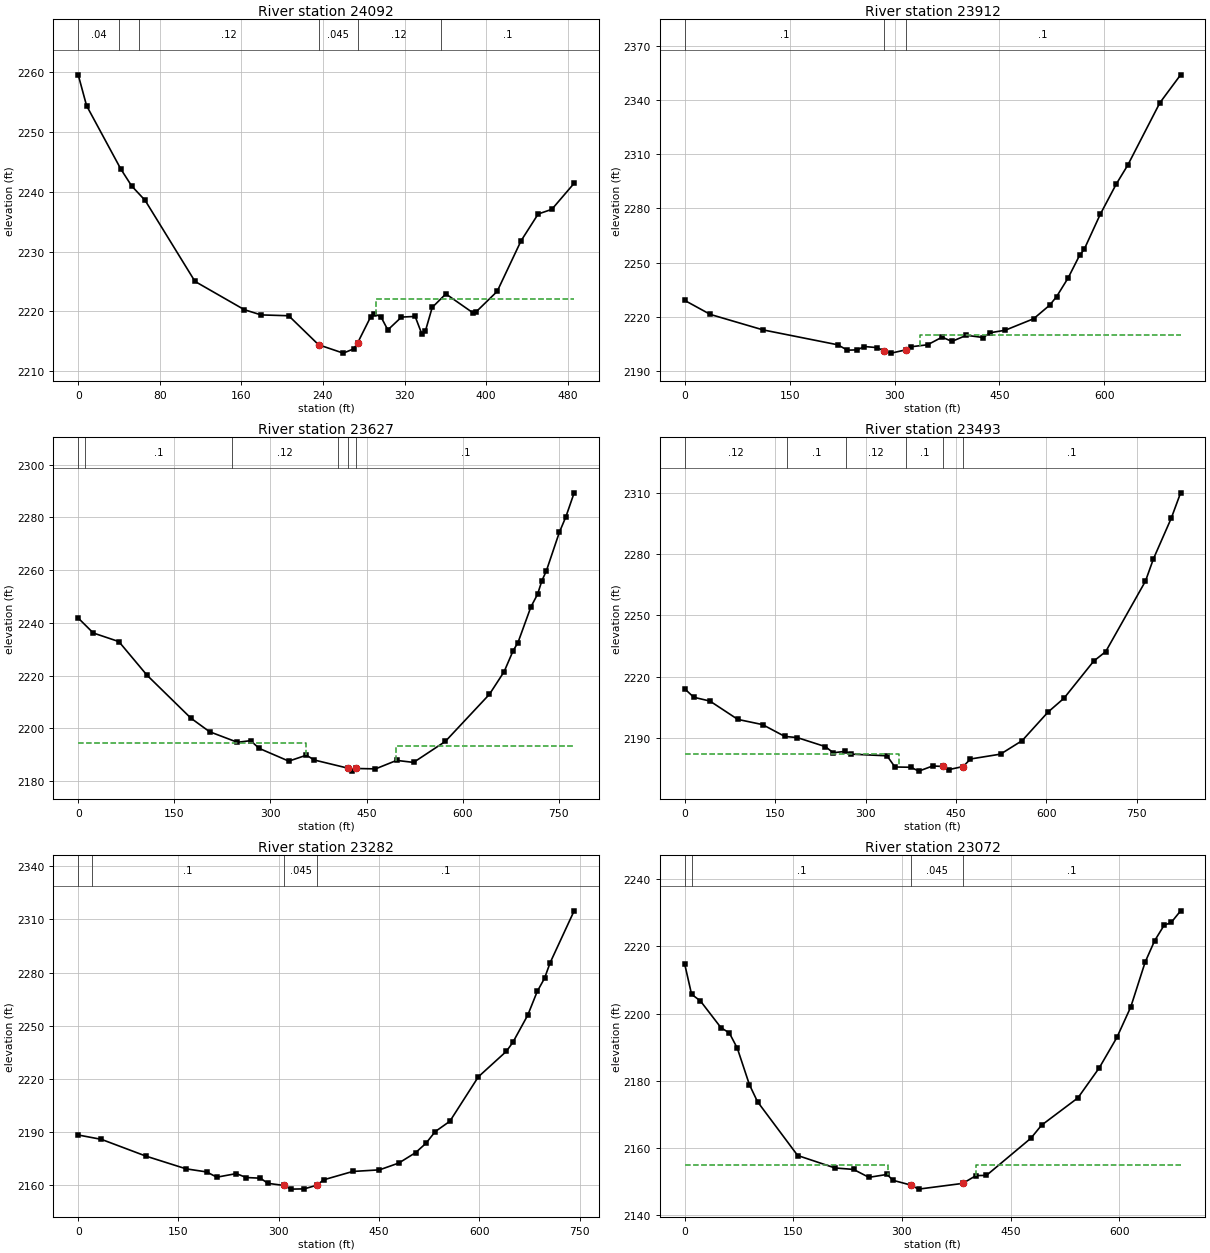
Type RM Length L Ch R = 1 ,24092   ,195.1,180.1,165.9
XS GIS Cut Line= 3
2009377.54622392 309246.287274962009275.37732947309191.988268297
2008912.43518763309117.075341445
#Sta/Elev= 30
       0 2259.54     8.2 2254.38    41.7 2243.81    52.4 2240.96    65.6 2238.55
   114.5    2225   162.9 2220.27   179.3  2219.4   206.4 2219.26   235.72214.406
   259.9 2213.01   270.1 2213.72   273.92214.688   286.8 2219.09   290.2 2219.59
   296.9 2219.06   303.6 2216.89     317 2219.04   330.4 2219.14   337.1 2216.14
   340.5 2216.74   347.1 2220.65   360.5 2222.91   387.3 2219.72   390.4 2219.95
   410.8 2223.33   434.2 2231.78     451 2236.27   464.4 2237.05   486.3 2241.41
#Mann= 6 ,-1 , 0
       0     .04       0      40      .1       0      60     .12       0
   235.7    .045       0   273.9     .12       0   355.7      .1       0
#XS Ineff= 2 , 0
                             292            2222
Permanent Ineff=
       F       F
Bank Sta=235.7,273.9
XS Rating Curve= 0 ,0
Exp/Cntr=0.3,0.1

Type RM Length L Ch R = 1 ,23912   ,274.6,285.7,289.3
XS GIS Cut Line= 4
2009415.11268674309005.0503379412009236.09774136 308950.43704508
2008959.00142013309045.9408732312008730.32980257309047.316670615
#Sta/Elev= 30
       0 2229.03    36.6 2221.26   112.1 2212.67   218.8 2204.42   232.6 2201.44
   246.5  2201.6   256.9 2203.46   274.3 2202.88     285 2201.13   295.1  2199.8
   315.9 2201.59   323.7 2203.34   347.2 2204.42     368 2208.67   381.9 2206.29
   402.7 2209.68   426.7 2208.45   436.8 2211.11   458.2  2212.5   498.8 2218.86
   521.7 2226.37   531.6 2231.11     548  2241.4   564.4 2253.94     571 2257.26
   593.9 2276.65   616.9 2293.52   633.3 2303.97   679.2 2338.54   708.9 2354.07
#Mann= 3 ,-1 , 0
       0      .1       0     285    .045       0   315.9      .1       0
#XS Ineff= 2 , 0
                             337            2210
Permanent Ineff=
       F       F
Bank Sta=285,315.9
XS Rating Curve= 0 ,0
Exp/Cntr=0.3,0.1

Type RM Length L Ch R = 1 ,23627   ,132.8,133.8,139.6
XS GIS Cut Line= 4
     2009519.457      308831.7982009252.89991406 308705.80696415
2008901.62681374308744.1465060732008780.38189919308777.461038357
#Sta/Elev= 30
       0 2241.83    23.5 2236.16    63.4  2232.9   107.2 2220.19   175.9 2203.85
   204.9 2198.72   248.5  2194.7   269.1 2195.33   282.2 2192.42   328.6 2187.56
   356.1 2189.82   368.2    2188   420.3 2184.93   427.6 2183.77   434.2 2184.77
   463.9 2184.62   496.9 2187.84   523.3 2187.08   572.8 2195.02   641.7 2212.91
   664.6 2221.48   678.6  2229.4   686.2 2232.51   706.4 2246.05   716.8 2250.85
   723.6    2256   730.5 2259.71   750.8 2274.34     761 2280.23   773.9 2289.32
#Mann= 6 ,-1 , 0
       0     .04       0      10      .1       0     240     .12       0
  404.83      .1       0   420.3    .045       0   434.2      .1       0
#XS Ineff= 2 , 0
          355.61 2194.47  496.19         2193.33
Permanent Ineff=
       F       F
Bank Sta=420.3,434.2
XS Rating Curve= 0 ,0
Exp/Cntr=0.3,0.1

Type RM Length L Ch R = 1 ,23493   ,217.4,210.4,191.9
XS GIS Cut Line= 3
2009506.27079616308623.6580646662009283.98602913308574.209077012
     2008692.231      308635.826
#Sta/Elev= 30
       0 2214.08      15 2209.93    41.9 2208.06    88.1 2199.08   129.2 2196.53
   166.2 2190.72   186.4  2190.2   233.3 2185.75   246.5 2182.75   266.3 2183.42
   276.2 2182.07   335.6 2181.24   348.8 2175.77   375.2 2175.63   388.4 2173.74
   411.5 2176.28   428.4 2176.01   437.8 2174.46     4622176.003   474.1 2179.68
     524 2182.07   559.9  2188.7   602.8 2202.68   629.2 2209.44   678.6 2227.65
   698.4 2232.27   764.4 2266.82   777.6 2277.73   807.3 2297.73   822.7 2310.07
#Mann= 6 ,-1 , 0
       0     .12       0     170      .1       0  267.72     .12       0
  367.72      .1       0   428.4    .045       0     462      .1       0
#XS Ineff= 2 , 0
           355.8    2182
Permanent Ineff=
       F       F
Bank Sta=428.4,462
XS Rating Curve= 0 ,0
Exp/Cntr=0.3,0.1

Type RM Length L Ch R = 1 ,23282   ,208.5,210.4,211.1
XS GIS Cut Line= 3
2009361.63098869308374.7141325232009182.91047947308339.089769856
     2008677.342      308578.993
#Sta/Elev= 30
       0 2188.44    34.7 2185.98   101.6 2176.49   161.4 2169.35   192.1 2167.61
   207.3 2164.65   236.5 2166.67   251.3 2164.45   272.6 2164.08   283.5 2161.19
   307.9 2159.96   317.7 2157.91     338 2158.05   357.12160.135     367 2163.15
   410.6 2167.87   450.6 2168.78   479.6 2172.64   504.7 2178.51     520 2183.71
   534.1 2190.39   555.9 2196.19   598.5 2221.26   640.4 2235.63   650.1 2240.68
   672.4 2256.04   686.6 2269.43   697.5 2276.83   705.8 2285.54   741.8 2314.88
#Mann= 4 ,-1 , 0
       0     .04       0      20      .1       0   307.9    .045       0
   357.1      .1       0
Bank Sta=307.9,357.1
XS Rating Curve= 0 ,0
Exp/Cntr(USF)=0,0
Exp/Cntr=0.3,0.1

Type RM Length L Ch R = 1 ,23072   ,187.5,190.2,193.6
XS GIS Cut Line= 4
2009243.45088114 308040.689718462009083.27749096308157.730777925
2008711.62433361308327.6941120822008660.48789674308386.213681441
#Sta/Elev= 30
       0 2214.71     9.5 2205.73    21.7 2203.74    50.2 2195.77    61.6 2194.25
    72.7 2189.68    89.4 2178.85   100.6 2173.79     156 2157.82   207.5 2154.12
   233.2 2153.68   254.4 2151.33   279.6  2152.2   287.3 2150.47     312 2149.05
   322.9 2147.83   383.9 2149.53   402.3 2151.85   416.7 2151.91   478.1 2162.96
   492.8 2166.83     543 2174.94   572.4 2183.84   596.8 2192.89     616 2201.97
   635.8 2215.25   648.9 2221.62     662 2226.22   671.8 2227.05   684.8 2230.51
#Mann= 4 ,-1 , 0
       0     .04       0      10      .1       0     312    .045       0
   383.9      .1       0
#XS Ineff= 2 , 0
             281    2155   402.7            2155
Permanent Ineff=
       F       F
Bank Sta=312,383.9
XS Rating Curve= 0 ,0
Exp/Cntr=0.3,0.1

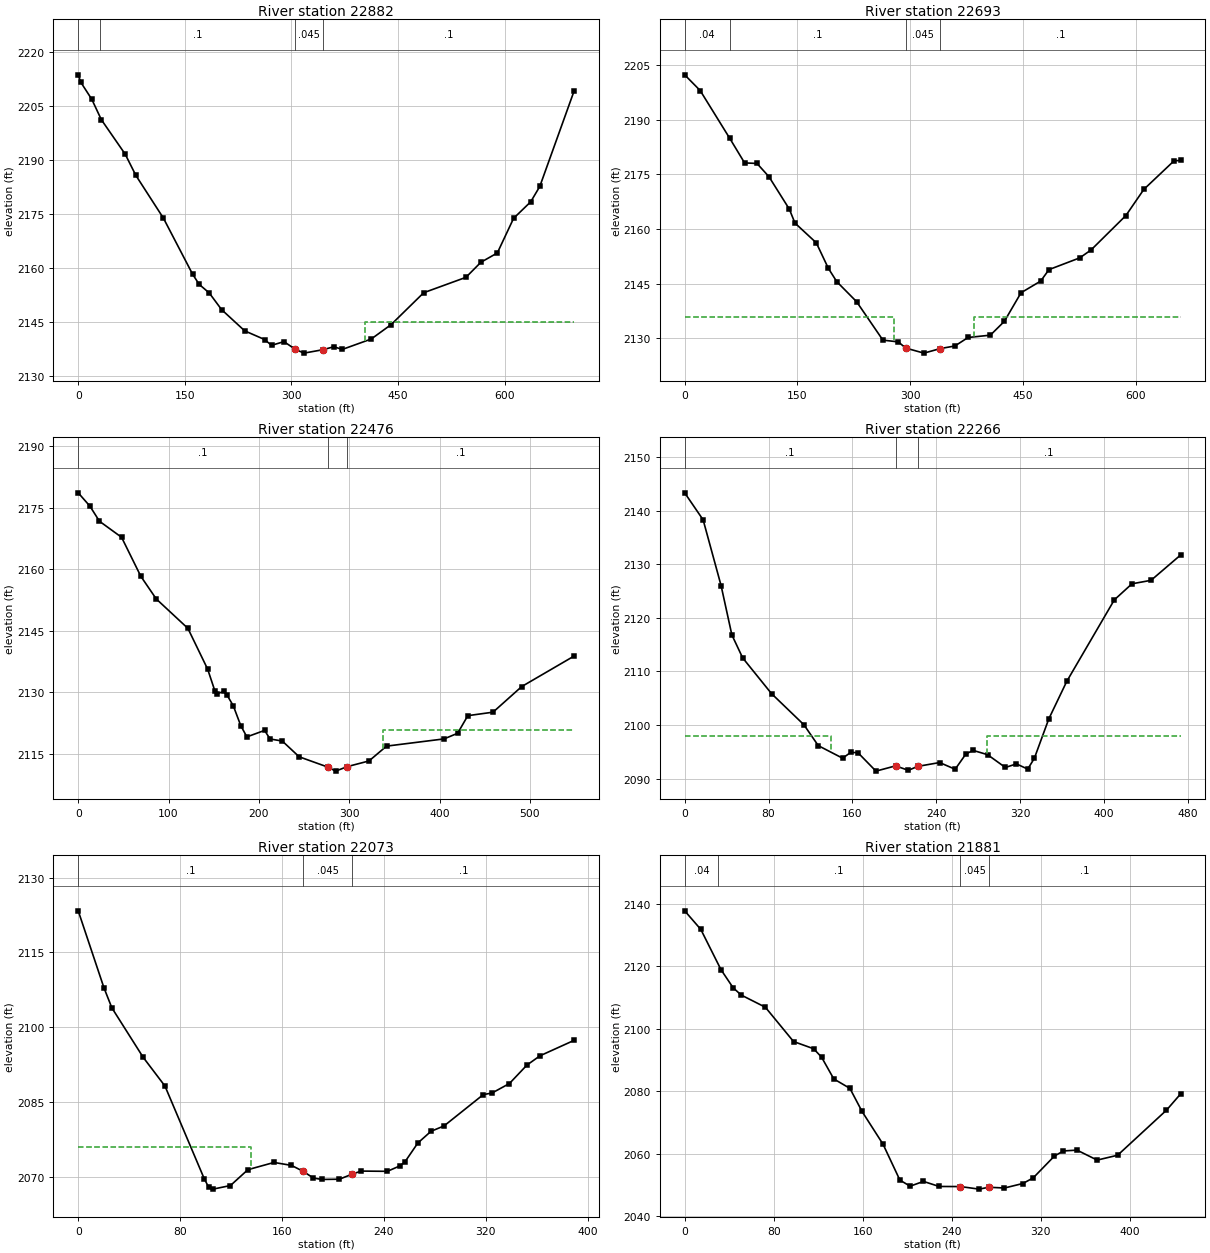
Type RM Length L Ch R = 1 ,22882   ,192.2,188.5,184.6
XS GIS Cut Line= 4
 2009169.8485996307897.4102518262009026.62304624307987.767443769
2008654.96988889308128.2704666722008570.96297078308228.965666831
#Sta/Elev= 30
       0 2213.53     3.5  2211.5    19.1 2206.74    32.5 2201.09    66.1  2191.5
    81.1 2185.61   119.9 2173.73   160.9 2158.19   170.2 2155.35   184.3 2152.98
   201.8 2148.33   234.2 2142.45   262.2 2140.04     272 2138.42   289.5 2139.45
   305.4 2137.33   317.6 2136.26   344.4 2137.21   359.6 2138.03   371.6 2137.29
   412.3 2140.18   440.4  2144.2   486.1 2153.03   545.5  2157.3   566.6 2161.49
   589.7 2164.07   612.6 2173.69   636.7 2178.28   649.5 2182.56   697.8 2209.09
#Mann= 4 ,-1 , 0
       0     .04       0      30      .1       0   305.4    .045       0
   344.4      .1       0
#XS Ineff= 2 , 0
                             403            2145
Permanent Ineff=
       F       F
Bank Sta=305.4,344.4
XS Rating Curve= 0 ,0
Exp/Cntr=0.3,0.1

Type RM Length L Ch R = 1 ,22693   ,218.4,216.8,214.1
XS GIS Cut Line= 4
2009102.13512567307794.7509264572008966.19163854307787.588405762
 2008611.9125109307975.6811622292008549.75485242308081.276496348
#Sta/Elev= 30
       0 2202.32    20.6 2198.01      60 2184.88    79.7 2178.15    96.2    2178
   112.1 2174.37   139.2 2165.47   146.7 2161.65   175.1 2156.22   191.2  2149.2
   202.4 2145.55   228.7 2140.07   263.7 2129.52   284.3 2129.03     294 2127.34
   318.3 2125.95   340.22127.206   359.5 2127.91     377 2130.24   406.7 2130.88
   425.3 2134.67   447.5 2142.52   473.6 2145.72   484.7 2148.87   525.6 2152.09
   540.7 2154.27     587 2163.71   610.9 2170.89   651.1 2178.73   659.8 2178.83
#Mann= 4 ,-1 , 0
       0     .04       0      60      .1       0     294    .045       0
   340.2      .1       0
#XS Ineff= 2 , 0
             278    2136   384.3            2136
Permanent Ineff=
       F       F
Bank Sta=294,340.2
XS Rating Curve= 0 ,0
Exp/Cntr=0.3,0.1

Type RM Length L Ch R = 1 ,22476   ,207.8,210.3,216.1
XS GIS Cut Line= 4
2008939.56917729307580.2975781842008807.55919333307628.955960549
2008546.94874762307773.2359464332008489.17719339 307867.39529615
#Sta/Elev= 30
       0 2178.59      13 2175.33    23.5 2171.67      48 2167.76    69.3 2158.26
    86.4 2152.74   121.4 2145.58   143.3 2135.63   151.4 2130.26   153.8 2129.67
   161.3  2130.2     165 2129.23   171.7  2126.7     180 2121.85   186.7 2119.14
   206.3 2120.72   212.4 2118.63   225.9 2118.13   244.6 2114.29     276 2111.81
     285  2110.8   297.7 2111.89   321.9 2113.28   341.3 2116.89     405 2118.65
     420 2120.02   431.3 2124.31   459.2 2125.16   490.9 2131.39     549 2138.84
#Mann= 3 ,-1 , 0
       0      .1       0     276    .045       0   297.7      .1       0
#XS Ineff= 2 , 0
                          337.54         2120.74
Permanent Ineff=
       F       F
Bank Sta=276,297.7
XS Rating Curve= 0 ,0
Exp/Cntr=0.3,0.1

Type RM Length L Ch R = 1 ,22266   ,193.7,192.7,192.5
XS GIS Cut Line= 3
2008763.68870094307461.7590859492008385.13334576307578.599767428
2008361.14407205307651.497708235
#Sta/Elev= 30
       0  2143.3    17.6 2138.26    34.7 2126.02      45 2116.81    55.3 2112.53
    82.8 2105.87   113.7 2100.06   127.4 2096.17   150.6 2093.83   158.3 2094.91
   165.2 2094.86   182.4 2091.42   201.1  2092.4   213.3 2091.57   222.1  2092.3
   243.1 2093.02   257.9 2091.77   268.2 2094.63   275.1 2095.28   288.8 2094.49
   305.8  2092.1   316.3 2092.77   327.1  2091.8   333.4  2093.8   347.2 2101.16
   364.3 2108.14   409.7 2123.35   426.5 2126.34   444.7 2126.99   472.9 2131.71
#Mann= 3 ,-1 , 0
       0      .1       0   201.1    .045       0   222.1      .1       0
#XS Ineff= 2 , 0
           139.4    2098   287.8            2098
Permanent Ineff=
       F       F
Bank Sta=201.1,222.1
XS Rating Curve= 0 ,0
Exp/Cntr=0.3,0.1

Type RM Length L Ch R = 1 ,22073   ,201.7,192.1,185.3
XS GIS Cut Line= 2
2008703.93799097307282.7161557692008330.82727858307393.640184419
#Sta/Elev= 30
       0 2123.34    20.2 2107.91    26.4 2103.89      51 2093.96    68.1  2088.2
    98.9 2069.63   102.3 2067.97   105.8 2067.53   119.5 2068.25   133.2 2071.43
   153.7 2072.88   167.4 2072.29   176.8 2071.07   184.5 2069.76   191.3 2069.47
     205 2069.52   215.3 2070.56   222.1 2071.15   242.7  2071.1   252.3 2072.17
   256.4 2072.97   266.6 2076.78   276.9 2079.12   287.2 2080.21     318 2086.49
   324.8  2086.8   338.5 2088.71   352.2  2092.4   362.5 2094.27   389.3 2097.37
#Mann= 3 ,-1 , 0
       0      .1       0   176.8    .045       0   215.3      .1       0
#XS Ineff= 2 , 0
           135.4    2076
Permanent Ineff=
       F       F
Bank Sta=176.8,215.3
XS Rating Curve= 0 ,0
Exp/Cntr(USF)=0,0
Exp/Cntr=0.3,0.1

Type RM Length L Ch R = 1 ,21881   ,187.4,192.8,196.2
XS GIS Cut Line= 3
2008674.76117492307034.3109087782008519.78378946 307106.80638584
2008297.54978734307268.054532871
#Sta/Elev= 30
       0 2137.73    14.5 2131.78    32.6 2118.92    43.5 2113.13    50.7  2110.8
    72.5 2106.88    97.8 2095.91   115.9 2093.59     123 2090.91     134 2083.94
   148.5 2080.91   159.4 2073.52   178.3 2063.02   193.4 2051.56   202.6 2049.61
   214.6 2051.14   228.7 2049.52   247.8 2049.49   264.6 2048.67   273.3 2049.27
   287.4 2049.03   303.9 2050.47   313.2 2052.26   332.3 2059.26   340.4 2060.89
   352.6 2061.15   370.7 2057.96   389.1 2059.52     433 2073.94   445.7 2079.14
#Mann= 4 ,-1 , 0
       0     .04       0      30      .1       0   247.8    .045       0
   273.3      .1       0
Bank Sta=247.8,273.3
XS Rating Curve= 0 ,0
Exp/Cntr=0.3,0.1

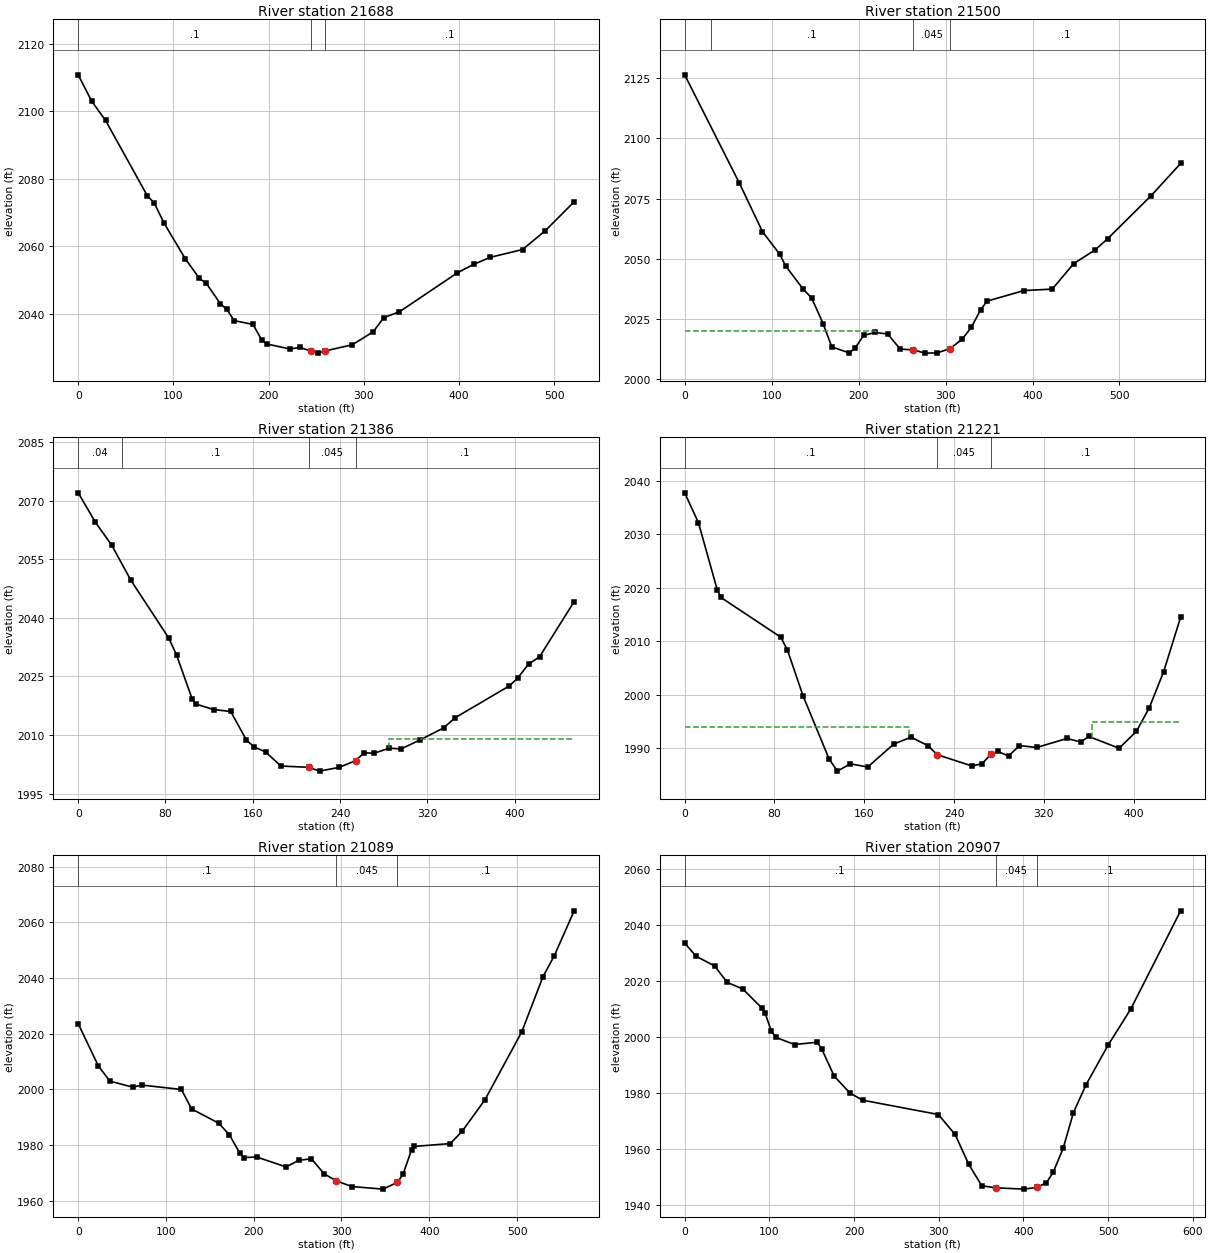
Type RM Length L Ch R = 1 ,21688   ,187.9,188.9,190.5
XS GIS Cut Line= 3
2008605.38393166306869.6948252022008302.16934352307017.902852587
2008250.58679237307193.957195204
#Sta/Elev= 30
       0 2110.83    14.1 2103.05    28.7 2097.33    72.5 2075.06    79.8 2072.88
    90.4  2066.8   112.5 2056.34   127.3 2050.53   134.6 2049.05   149.2 2043.09
   156.2 2041.36   163.8 2038.04   183.6  2036.9     193  2032.2   198.3  2031.1
   222.3 2029.63   233.2 2030.09   244.2 2028.99   251.5  2028.4   259.7 2029.07
     288 2030.88   309.9 2034.72     321 2038.92   337.5 2040.65   398.4 2052.21
   415.5  2054.7   432.6 2056.76   466.8 2059.08   490.8  2064.7     521 2073.22
#Mann= 3 ,-1 , 0
       0      .1       0   244.2    .045       0   259.7      .1       0
Bank Sta=244.2,259.7
XS Rating Curve= 0 ,0
Exp/Cntr=0.3,0.1

Type RM Length L Ch R = 1 ,21500   ,113.7,113.4,113.8
XS GIS Cut Line= 3
2008579.21319946306747.1758538312008365.39570383306782.673598114
2008039.59760075306920.063314044
#Sta/Elev= 30
       0 2126.36    62.8 2081.47    89.4 2061.29   109.4 2051.83     116 2047.06
     136  2037.5     146 2033.71   159.3 2022.97   169.2 2013.38   189.2 2010.91
   195.8 2012.82   205.8 2018.19   219.3 2019.41   233.5 2018.72   247.8 2012.51
     2632012.136   276.3 2010.81   290.5  2010.9     305 2012.69     319 2016.53
   329.7 2021.57   340.3 2028.78   347.8 2032.41   390.2 2036.79   422.7 2037.39
   447.2 2047.93   472.1  2053.7   486.3 2058.28   536.2 2076.12   570.3 2089.55
#Mann= 4 ,-1 , 0
       0     .04       0      30      .1       0     263    .045       0
     305      .1       0
#XS Ineff= 2 , 0
             220    2020
Permanent Ineff=
       F       F
Bank Sta=263,305
XS Rating Curve= 0 ,0
Exp/Cntr=0.3,0.1

Type RM Length L Ch R = 1 ,21386   ,169.9,164.7,158.5
XS GIS Cut Line= 2
2008489.07342596306611.2295175862008068.55608998306783.887186596
#Sta/Elev= 30
       0 2071.97    15.6 2064.51    30.7 2058.57    48.3 2049.58      83  2034.8
    90.1 2030.49   104.3 2019.33   107.9 2017.91   124.1 2016.51   139.8 2016.01
   154.2 2008.69   161.1 2006.98   171.7 2005.65   185.9 2002.05   211.32001.736
   221.3 2000.75   239.1 2001.71   254.4 2003.43     262 2005.46     271  2005.3
   285.2 2006.63   295.8 2006.42   313.6 2008.76   334.9 2011.81   345.5 2014.41
   394.9 2022.51   402.8 2024.55   412.8 2028.13   422.9 2030.02   454.6 2044.13
#Mann= 4 ,-1 , 0
       0     .04       0      40      .1       0   211.3    .045       0
   254.4      .1       0
#XS Ineff= 2 , 0
                             285            2009
Permanent Ineff=
       F       F
Bank Sta=211.3,254.4
XS Rating Curve= 0 ,0
Exp/Cntr=0.3,0.1

Type RM Length L Ch R = 1 ,21221   ,139.4,132.5,125.2
XS GIS Cut Line= 3
2008450.68009838306461.8556562532008321.55758706306483.040268008
2008057.32560892306647.105875349
#Sta/Elev= 30
       0 2037.72    12.3 2032.12      29 2019.62    32.3 2018.18    85.5 2010.78
    91.5 2008.41   105.4 1999.84   128.8 1987.96   136.1 1985.75   147.7 1987.11
   163.1 1986.52   186.3  1990.8   201.7 1992.09   217.2 1990.46   224.71988.847
   255.8 1986.72   264.8  1987.1     273 1988.92   279.1 1989.42   288.6 1988.57
   298.3 1990.52   313.7 1990.17   340.7 1991.85   352.9 1991.19   360.1 1992.22
   387.1 1990.02   402.5 1993.17   414.1 1997.63   426.8 2004.34   441.9 2014.49
#Mann= 3 ,-1 , 0
       0      .1       0   224.7    .045       0     273      .1       0
#XS Ineff= 2 , 0
             200    1994  362.89         1994.92
Permanent Ineff=
       F       F
Bank Sta=224.7,273
XS Rating Curve= 0 ,0
Exp/Cntr(USF)=0,0
Exp/Cntr=0.3,0.1

Type RM Length L Ch R = 1 ,21089   ,175.7,181.7,186.8
XS GIS Cut Line= 3
2008405.63247983306298.0058139892008287.89242346306302.697142455
2007961.56282187306608.631143937
#Sta/Elev= 30
       0 2023.59    22.9 2008.47      36 2002.99    62.3  2000.8    72.2 2001.57
   117.6 1999.99   129.2 1992.99   160.2 1987.86   172.2 1983.72   184.1 1977.15
   188.9 1975.54   203.3 1975.75   236.9 1972.17   251.3 1974.55   265.7 1975.09
   280.1 1969.75   293.6 1967.22   311.6 1965.14   347.2  1964.2   363.7 1966.62
   370.1 1969.56   379.9 1978.34   382.2 1979.52     424 1980.56   437.5 1984.97
   463.5 1996.32   505.3  2020.6   529.5 2040.44   542.4 2047.97   565.1 2064.14
#Mann= 3 ,-1 , 0
       0      .1       0   293.6    .045       0   363.7      .1       0
Bank Sta=293.6,363.7
XS Rating Curve= 0 ,0
Exp/Cntr=0.3,0.1

Type RM Length L Ch R = 1 ,20907   ,163.2,170.7,176
XS GIS Cut Line= 3
2008358.07971987306115.1567734062008095.49392919306255.107408891
2007858.68693426306418.890586159
#Sta/Elev= 30
       0 2033.45    13.3 2028.76    35.3 2025.26    50.1 2019.42    68.7    2017
      91 2010.25    94.7 2008.62   102.2 2002.05   107.8 1999.72   129.7 1997.18
   156.4 1998.01   161.7 1995.65   176.5 1985.91   195.1 1979.85     210 1977.31
   299.4 1972.19   319.3 1965.05   335.2 1954.48   350.8 1946.71   367.2    1946
   400.8 1945.53   415.5 1946.14     427 1947.78     435 1951.51   446.9 1960.17
   458.9 1972.83   473.9 1982.83   499.8 1996.93   526.7  2009.9   585.5 2044.95
#Mann= 3 ,-1 , 0
       0      .1       0   367.2    .045       0   415.5      .1       0
Bank Sta=367.2,415.5
XS Rating Curve= 0 ,0
Exp/Cntr=0.3,0.1

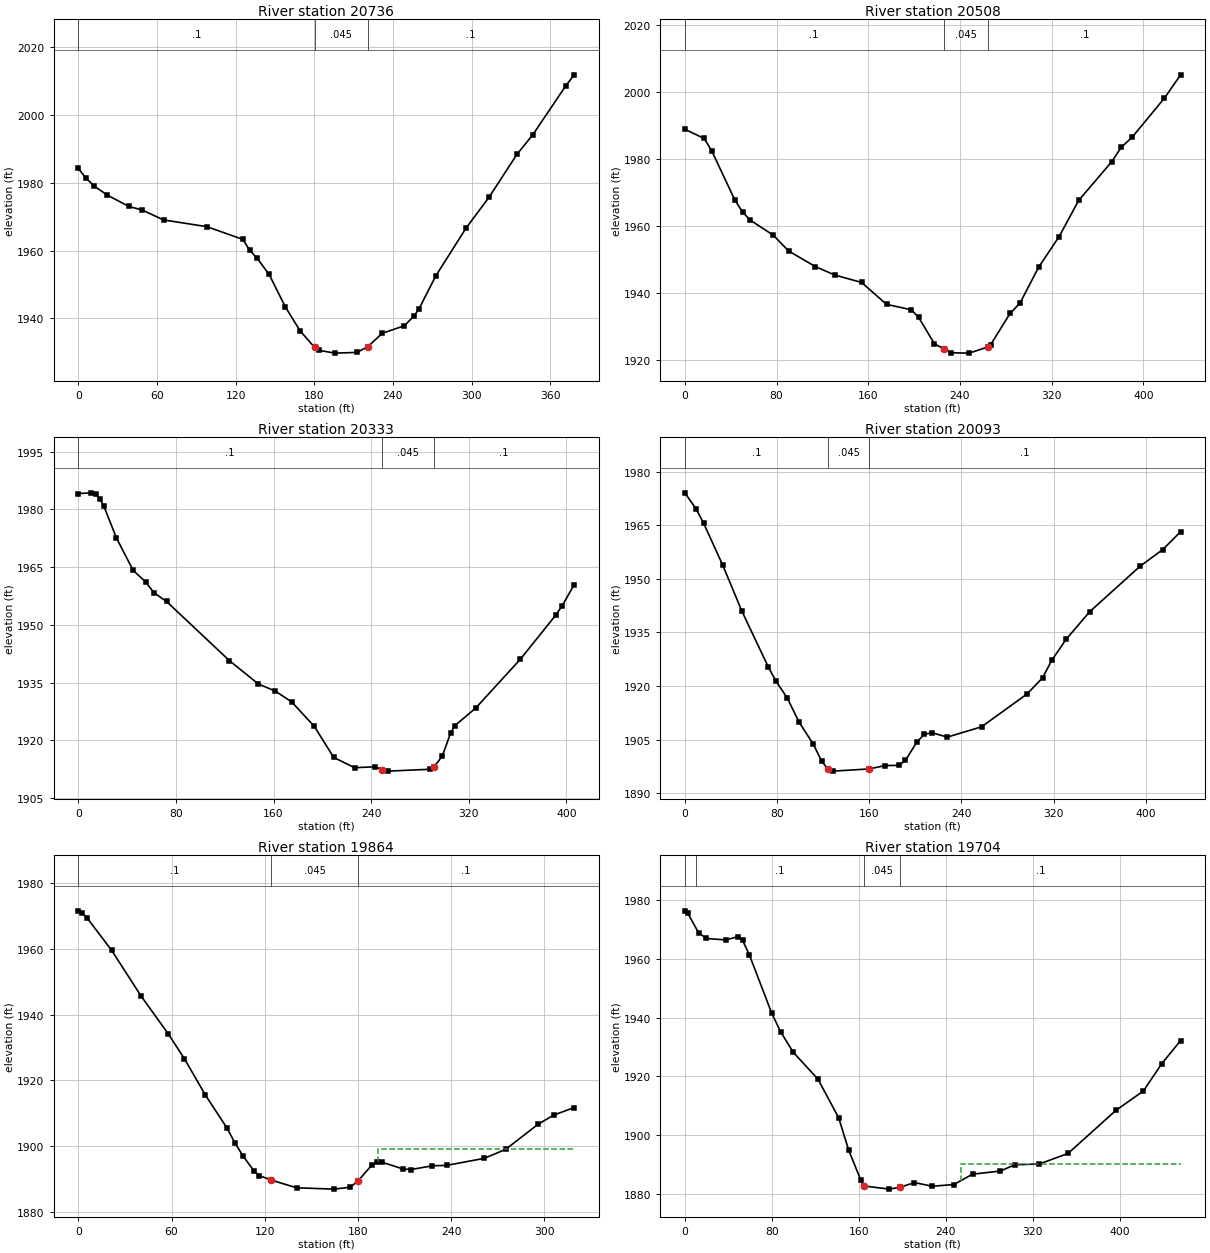
Type RM Length L Ch R = 1 ,20736   ,236,228.6,220.7
XS GIS Cut Line= 3
2008165.07356892306124.4854802992008052.21832668306109.861266553
2007812.78399864306222.176921203
#Sta/Elev= 30
       0 1984.26     5.5 1981.54    12.1 1979.07      22 1976.41    38.6 1973.03
    48.5 1972.03      65 1969.07    98.2 1967.06   125.6  1963.3   130.7  1960.1
   136.5 1957.71   145.6 1952.95   157.8 1943.48   169.1 1936.36   180.2 1931.45
   183.6 1930.55   195.7 1929.73   212.6 1929.94   220.7 1931.58   231.9 1935.59
   248.8 1937.82   256.1 1940.71   259.7 1942.66   272.9 1952.65   295.9  1966.7
   313.3 1975.72   334.7 1988.47   346.7 1994.18     372 2008.72   378.3 2011.91
#Mann= 3 ,-1 , 0
       0      .1       0   180.2    .045       0   220.7      .1       0
Bank Sta=180.2,220.7
XS Rating Curve= 0 ,0
Exp/Cntr=0.3,0.1

Type RM Length L Ch R = 1 ,20508   ,162.5,174.4,187.1
XS GIS Cut Line= 4
2008077.72557247 305869.533946962007912.91912027305903.518066485
2007796.35846107306002.8818210022007727.81945442306090.212999753
#Sta/Elev= 30
       0 1988.81    16.9 1986.05    23.6 1982.28    43.7 1967.63    50.4 1964.07
    57.1 1961.64    77.2 1957.15    90.6 1952.42     114 1947.75   130.8 1945.25
   154.2 1943.03     176 1936.48   197.6 1934.86   203.9 1932.64   217.8 1924.66
   225.81923.224   232.1 1922.02   248.1 1921.91   264.4 1923.76   266.9 1924.48
   283.8 1933.82   292.3 1936.81   308.6 1947.55   326.5 1956.72   343.6 1967.56
   372.4  1979.1   380.7  1983.4   390.3 1986.47   418.4 1998.12   432.5 2005.07
#Mann= 3 ,-1 , 0
       0      .1       0   225.8    .045       0   264.4      .1       0
Bank Sta=225.8,264.4
XS Rating Curve= 0 ,0
Exp/Cntr=0.3,0.1

Type RM Length L Ch R = 1 ,20333   ,233.8,240.8,261.4
XS GIS Cut Line= 2
2008041.93929226305717.4945590422007652.42726553305833.563259123
#Sta/Elev= 30
       0 1984.09    10.7 1984.28    14.1 1983.93    17.5 1982.79      21 1980.75
    31.2 1972.59    44.9 1964.15    55.2 1961.12      62 1958.34    72.3 1956.06
   123.7 1940.73   147.6 1934.62   161.3 1932.81   174.9 1929.97   193.4 1923.63
   209.3 1915.56   226.4 1912.89   243.5 1913.13   248.8 1912.42   253.8    1912
     288 1912.48   291.4 1913.02   298.3 1915.91   305.1 1921.85   308.5 1923.79
   325.6 1928.35   362.2 1941.02   391.2 1952.47   396.5 1954.91   406.4 1960.41
#Mann= 3 ,-1 , 0
       0      .1       0   248.8    .045       0   291.4      .1       0
Bank Sta=248.8,291.4
XS Rating Curve= 0 ,0
Exp/Cntr=0.3,0.1

Type RM Length L Ch R = 1 ,20093   ,240.7,228.4,217.5
XS GIS Cut Line= 3
2008011.90576246305588.8934136822007703.52428897305554.016937513
2007607.63126889 305625.67529651
#Sta/Elev= 30
       0 1974.06     9.8 1969.56    16.4 1965.51    32.9 1953.83    49.4 1941.03
    72.5 1925.29    79.1 1921.38      89 1916.59      99 1909.99   111.5 1903.71
   118.8 1898.97   124.2 1896.75   128.7  1896.2   160.21896.822   173.8 1897.76
   185.6 1897.81   191.4  1899.2   201.3 1904.34   207.9 1906.54   214.5 1906.93
   227.7 1905.72   257.4 1908.59   297.1 1917.84   310.3  1922.3   318.4 1927.23
   330.7 1933.05   351.2 1940.79   394.7 1953.46   414.6 1958.19   430.1 1963.19
#Mann= 3 ,-1 , 0
       0      .1       0   124.2    .045       0   160.2      .1       0
Bank Sta=124.2,160.2
XS Rating Curve= 0 ,0
Exp/Cntr=0.3,0.1

Type RM Length L Ch R = 1 ,19864   ,146.4,160.4,170.8
XS GIS Cut Line= 2
2007961.87973057305312.9301420062007658.37504975305411.742523945
#Sta/Elev= 30
       0 1971.49     2.5 1970.83     5.9 1969.17    21.4 1959.52    40.4 1945.61
    57.9 1934.14    68.3  1926.6    81.8 1915.56    95.7 1905.55   100.7 1901.14
     106 1897.09   112.9 1892.66   116.4 1891.14     124 1889.78   140.5 1887.42
   164.6 1887.01     175 1887.59     1801889.455   188.8 1894.23   192.3 1895.15
   195.8 1895.13   208.8 1893.17     214 1892.94   227.9 1894.09   237.1 1894.22
   261.3 1896.35   275.1 1899.08   295.8 1906.65   306.1  1909.5   319.2 1911.77
#Mann= 3 ,-1 , 0
       0      .1       0     124    .045       0     180      .1       0
#XS Ineff= 2 , 0
                          192.71         1899.22
Permanent Ineff=
       F       F
Bank Sta=124,180
XS Rating Curve= 0 ,0
Exp/Cntr=0.3,0.1

Type RM Length L Ch R = 1 ,19704   ,189.2,173.5,156.5
XS GIS Cut Line= 4
2007967.87629087      305168.5252007870.56425378305211.370855853
2007672.92526741305197.8597360062007552.19596481305289.292407721
#Sta/Elev= 30
       0 1976.43     2.7 1975.68    12.6 1968.97    19.9    1967    37.8 1966.51
    48.6 1967.61    53.1 1966.38    59.3 1961.49    79.8 1941.64      88 1935.28
    99.7 1928.22   122.4 1919.08   141.5 1905.86   150.7 1894.83   161.9 1884.59
   165.2 1882.61   188.2 1881.56     198 1882.21   211.2 1883.78   227.6 1882.54
   247.4 1883.13   264.6 1886.66   290.1 1887.72   303.3 1889.85     326 1890.14
   352.4 1893.72   396.3 1908.38   421.7 1915.03   438.4 1924.25   455.9 1932.19
#Mann= 4 ,-1 , 0
       0     .04       0      10      .1       0   165.2    .045       0
     198      .1       0
#XS Ineff= 2 , 0
                             254            1890
Permanent Ineff=
       F       F
Bank Sta=165.2,198
XS Rating Curve= 0 ,0
Exp/Cntr=0.3,0.1