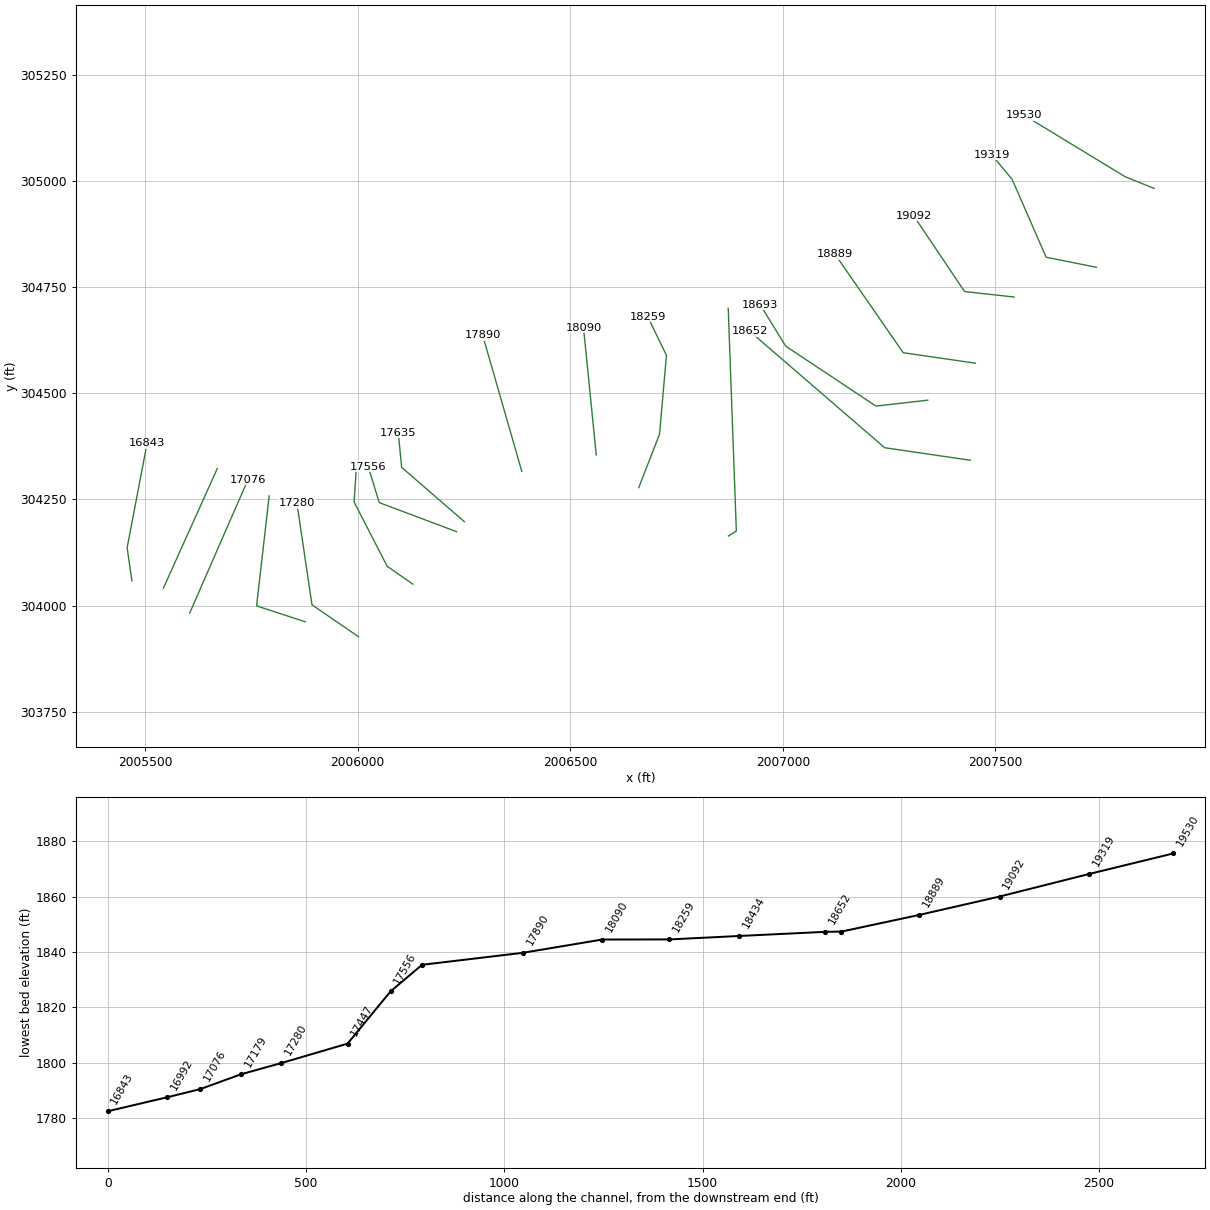
HEC-RAS study MEADOWCK_A.prj: MEADOWCK_A

--- MEADOWCK_A.g01 (geometry) --- (continued)

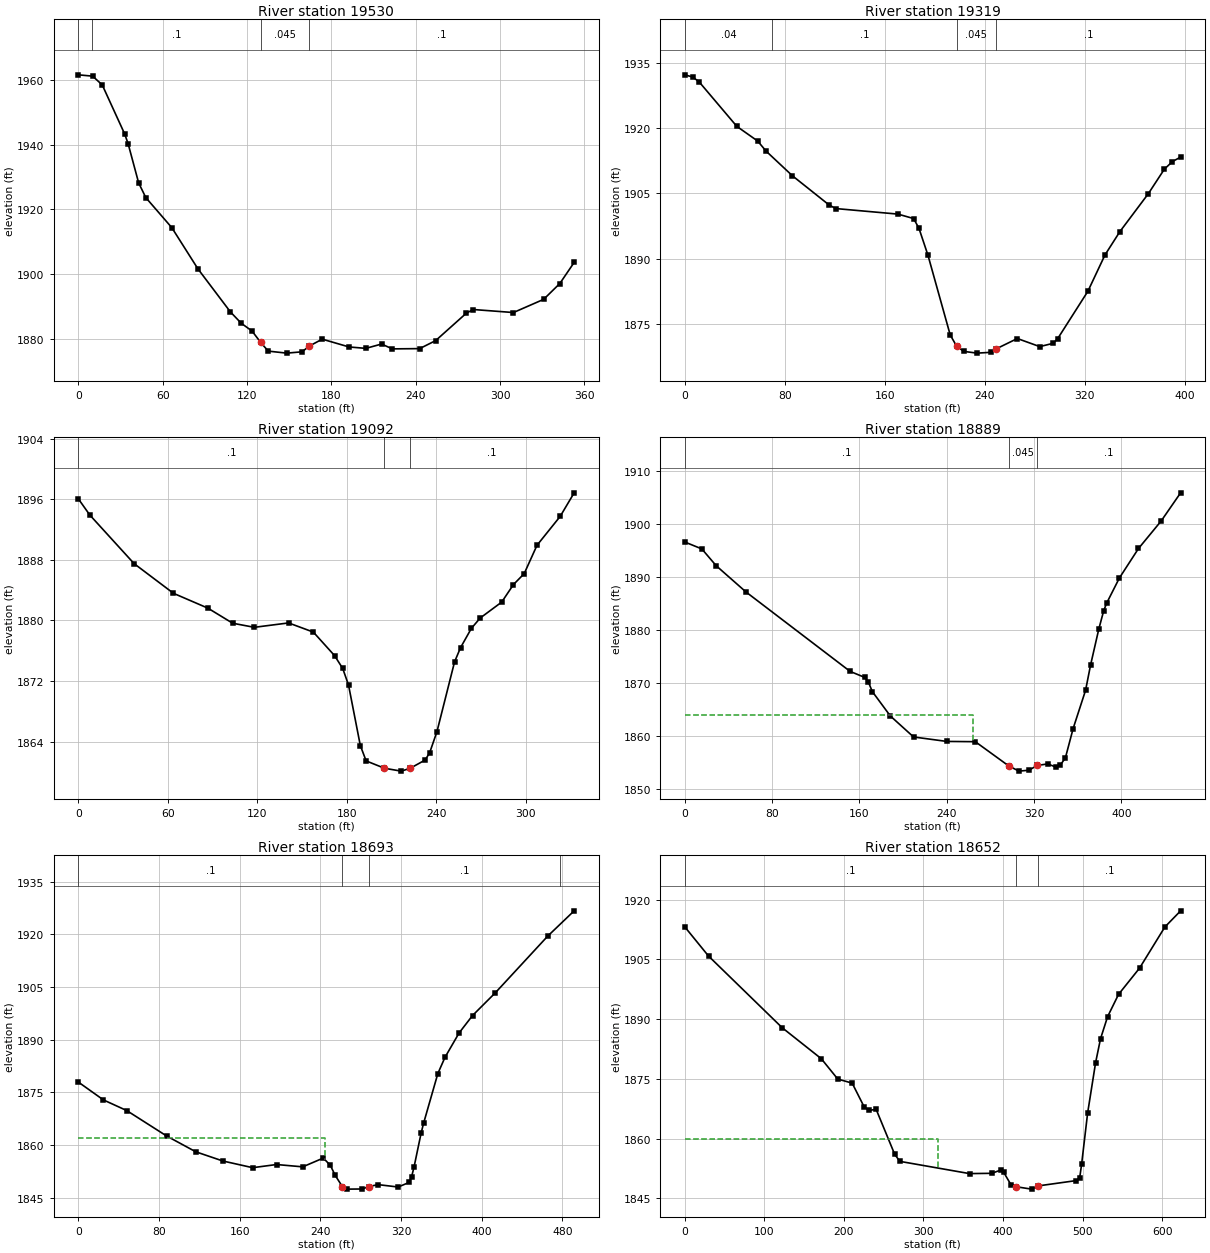
Type RM Length L Ch R = 1 ,19530   ,228.3,211.7,195.6
XS GIS Cut Line= 3
2007873.54771702304982.4338062232007805.44877645305009.961957875
 2007566.9713338305155.186184507
#Sta/Elev= 30
       0 1961.53    10.2 1961.12      17 1958.42    32.9 1943.35    35.4 1940.31
    42.9  1928.2      48 1923.66    66.5 1914.39    85.1 1901.66   108.2 1888.39
   115.9  1884.9   123.6 1882.49   129.7 1878.99   135.1 1876.31   148.2 1875.69
   159.1 1876.09   164.31877.868   173.5    1880   192.6 1877.59   204.5 1877.16
   215.7 1878.49   223.4    1877   242.8 1877.08   254.2 1879.56   276.1 1888.05
     281 1889.14   309.5 1888.21     331 1892.28   342.5 1897.16   352.7 1903.67
#Mann= 4 ,-1 , 0
       0     .04       0      10      .1       0   129.7    .045       0
   164.3      .1       0
Bank Sta=129.7,164.3
XS Rating Curve= 0 ,0
Exp/Cntr=0.3,0.1

Type RM Length L Ch R = 1 ,19319   ,222.4,226.6,229.9
XS GIS Cut Line= 4
2007737.83778519304796.6720233972007619.58442813304820.396185846
2007539.51281293305003.9565867352007490.97886752305062.071961993
#Sta/Elev= 30
       0 1932.28     6.4 1931.77    11.5 1930.65    41.6 1920.43    58.3 1917.05
      65 1914.74    86.1 1909.06   115.2  1902.4   120.6 1901.53   170.5 1900.25
     183 1899.23   187.3 1896.99   194.5 1890.79   212.3 1872.46   217.4 1869.89
   223.1 1868.68   233.8 1868.28   244.6 1868.46     249 1869.25     266 1871.64
   283.9 1869.78   294.7 1870.54   298.3 1871.63   322.4  1882.5   336.1 1890.86
     348 1896.22   370.8 1904.96   383.6 1910.59     390 1912.32   396.6 1913.37
#Mann= 4 ,-1 , 0
       0     .04       0      70      .1       0   217.4    .045       0
     249      .1       0
Bank Sta=217.4,249
XS Rating Curve= 0 ,0
Exp/Cntr=0.3,0.1

Type RM Length L Ch R = 1 ,19092   ,202.7,203.1,203.3
XS GIS Cut Line= 3
2007543.96469605304726.7188456082007427.71470869304739.569178047
2007307.60728588304918.597223358
#Sta/Elev= 30
       0 1896.05     7.7 1893.91    37.4 1887.49    63.8 1883.57    86.9 1881.61
   103.5 1879.62     118 1879.08     141 1879.66   157.6 1878.45   171.8 1875.35
   177.3 1873.65   181.2 1871.45   189.1 1863.47     193 1861.44   205.3 1860.47
   216.5 1860.09   222.4 1860.45   232.6 1861.56   235.6 1862.52   240.5 1865.31
   252.3 1874.52   256.3 1876.39   263.6 1878.95   269.5 1880.31   283.9 1882.41
   291.8 1884.73     299 1886.17   307.6 1889.92   323.1 1893.72   332.5 1896.84
#Mann= 3 ,-1 , 0
       0      .1       0   205.3    .045       0   222.4      .1       0
Bank Sta=205.3,222.4
XS Rating Curve= 0 ,0
Exp/Cntr=0.3,0.1

Type RM Length L Ch R = 1 ,18889   ,186.4,195.8,203.9
XS GIS Cut Line= 3
2007453.26394057304570.885052617 2007283.3776152304595.564969792
 2007122.5360998304827.950111808
#Sta/Elev= 30
       0 1896.55    15.6 1895.25    28.8 1892.08    56.1 1887.14   151.5 1872.19
   164.8 1871.07   168.1 1870.24   171.8  1868.4   188.3 1863.81   209.6 1859.85
   240.1 1859.01   266.2 1858.96   296.8  1854.4   306.2 1853.42   315.3 1853.59
   322.8 1854.48   332.6 1854.78   339.9 1854.18     344 1854.55   348.7  1855.9
   355.8 1861.43   367.2 1868.63   371.8 1873.41   379.3 1880.14   383.8  1883.6
   386.4 1884.99   398.2 1889.78   415.7 1895.33   436.4 1900.49   454.3 1905.81
#Mann= 3 ,-1 , 0
       0      .1       0   296.8    .045       0   322.8      .1       0
#XS Ineff= 2 , 0
             264    1864
Permanent Ineff=
       F       F
Bank Sta=296.8,322.8
XS Rating Curve= 0 ,0
Exp/Cntr=0.3,0.1

Type RM Length L Ch R = 1 ,18693   ,44.8,41.5,38.9
XS GIS Cut Line= 4
2007341.15881441304483.8433044432007219.22635212304469.894021184
 2007006.8325996304611.045052123  2006947.162208304708.257391608
#Sta/Elev= 30
       0 1877.92    24.9 1872.83      48  1869.8    87.6 1862.55   116.5 1858.05
   143.3 1855.43   172.9 1853.52   196.6 1854.42   222.6 1853.76     243 1856.27
     250 1854.17   254.8 1851.32     262 1848.08   266.7 1847.41   281.7 1847.45
   288.21848.157   297.4 1848.69   317.2 1848.01   328.2 1849.33   330.6 1850.99
   332.9 1853.61     340 1863.37   342.4 1866.13   356.6 1880.35   363.7 1884.98
   377.7 1891.93     391 1896.88   413.7 1903.39   465.6 1919.52   491.8 1926.72
#Mann= 4 ,-1 , 0
       0      .1       0     262    .045       0   288.2      .1       0
  477.75     .08       0
#XS Ineff= 2 , 0
             245    1862
Permanent Ineff=
       F       F
Bank Sta=262,288.2
XS Rating Curve= 0 ,0
Exp/Cntr=0.3,0.1

Type RM Length L Ch R = 1 ,18652   ,241.8,217.3,200
XS GIS Cut Line= 3
2007441.12244627304342.4004141242007239.73355734304371.914303005
  2006922.025224304646.219858572
#Sta/Elev= 30
       0 1913.17    29.8 1905.85   122.4 1887.85   171.6 1880.06   192.3 1874.95
   210.4 1873.93   225.3 1868.03   231.3  1867.1   240.6 1867.32   263.9 1856.03
   270.4 1854.28   357.9 1851.21   385.9 1851.28   396.9 1852.08     401 1851.49
   409.9 1848.46   416.91847.897   435.9 1847.31   444.2 1848.12   492.3 1849.46
   496.4 1850.15   498.8 1853.51   506.4 1866.43   516.4 1879.06   522.6 1885.07
   531.5 1890.62   545.3 1896.23   571.7 1902.82   603.5 1913.14   623.3  1917.2
#Mann= 3 ,-1 , 0
       0      .1       0   416.9    .045       0   444.2      .1       0
#XS Ineff= 2 , 0
             318    1860
Permanent Ineff=
       F       F
Bank Sta=416.9,444.2
XS Rating Curve= 0 ,0
Exp/Cntr(USF)=0,0
Exp/Cntr=0.3,0.1

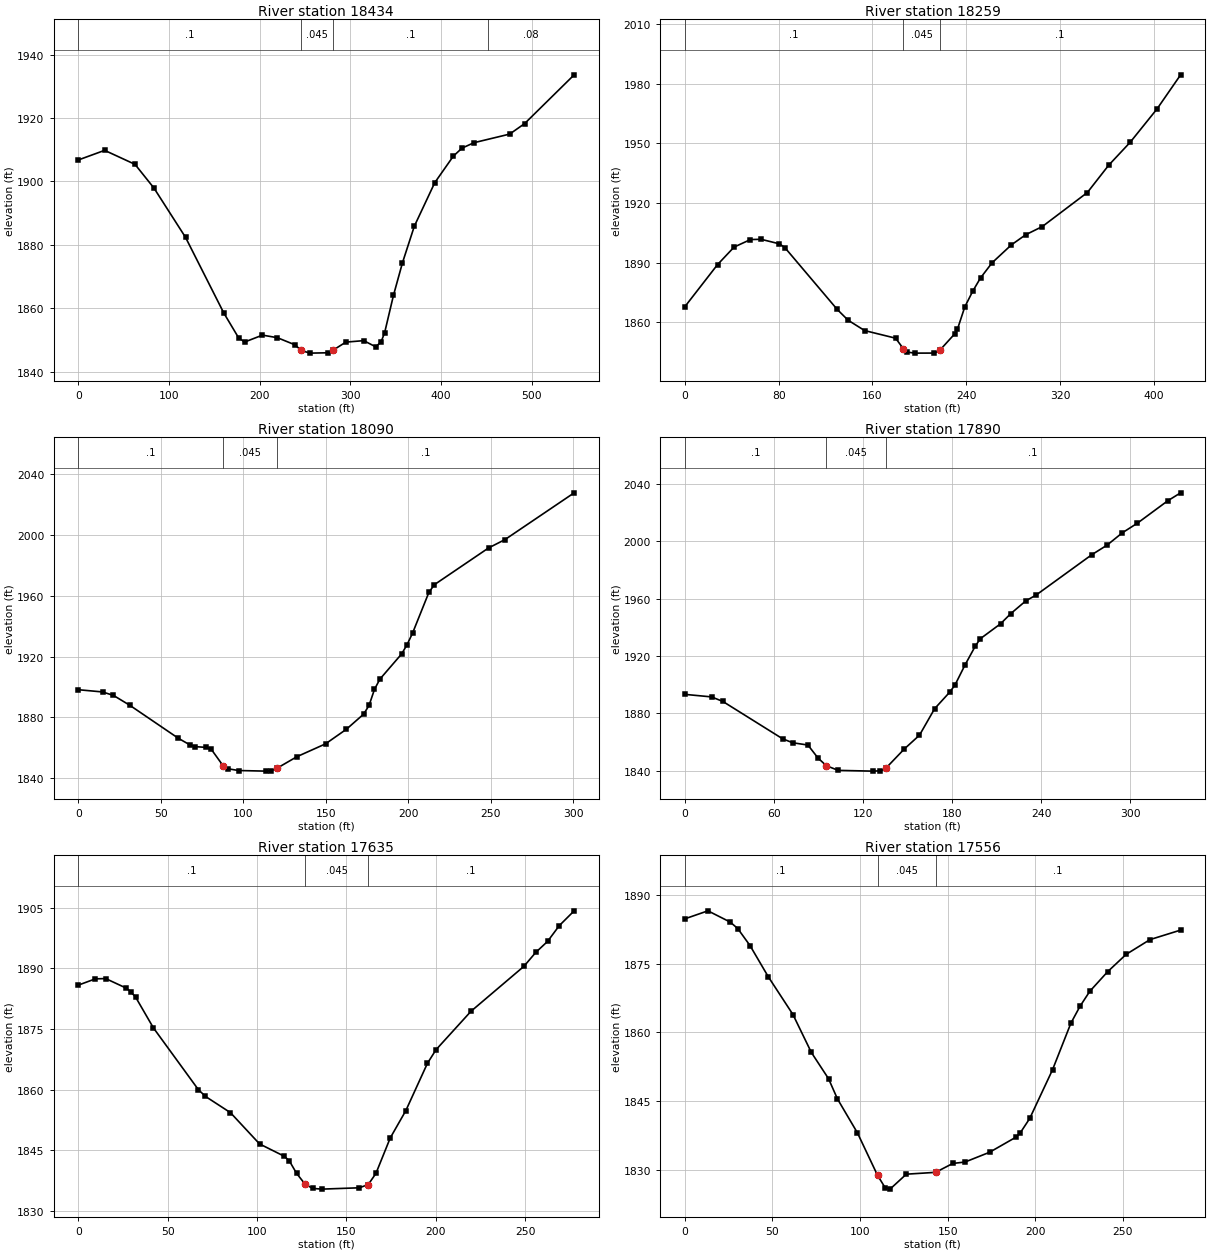
Type RM Length L Ch R = 1 ,18434   ,180.5,175.1,173.1
XS GIS Cut Line= 3
2006872.13476525304164.0551635272006890.77522403304175.733747453
2006871.67800179304700.039303005
#Sta/Elev= 30
       0 1906.76      29 1909.79    62.5 1905.37    83.4 1897.88   118.2 1882.33
   160.3  1858.5   176.7 1850.63   183.3 1849.31     203 1851.49   219.4 1850.68
   239.1  1848.4   245.6 1846.64   255.5 1845.81   275.2 1845.92   280.51846.684
   294.9 1849.28   314.6 1849.75   327.7 1847.82   333.6 1849.27   337.6 1852.18
   347.4 1864.04   357.3  1874.3   370.4 1885.85   392.9 1899.58   413.4 1907.96
   422.9 1910.48   436.1  1912.2   475.5 1914.92   491.9 1918.21   546.6 1933.62
#Mann= 4 ,-1 , 0
       0      .1       0   245.6    .045       0   280.5      .1       0
     452     .08       0
Bank Sta=245.6,280.5
XS Rating Curve= 0 ,0
Exp/Cntr(USF)=0,0
Exp/Cntr=0.3,0.1

Type RM Length L Ch R = 1 ,18259   ,162.8,169.2,172.7
XS GIS Cut Line= 4
 2006661.1997369 304278.099858342006710.07588926304403.962660211
 2006726.3272788304589.3490305762006682.00576778304680.727031033
#Sta/Elev= 30
       0 1867.87    27.9 1889.06      42 1897.87      56 1901.66      65 1901.79
    80.7  1899.5    85.3 1897.61   129.9 1866.56   139.2 1861.12   153.3 1855.91
   179.7 1852.08   186.3 1846.82   189.6 1845.08   196.1 1844.57   212.6  1844.6
   217.31845.943   230.1 1854.25   232.4 1856.52   238.7  1867.8   245.5 1875.73
   252.1 1882.37     262    1890   278.4 1898.98   290.6 1904.07   304.8  1908.2
   343.2 1925.31   361.4 1939.04   379.7 1950.56   402.6 1967.33   422.7 1984.46
#Mann= 3 ,-1 , 0
       0      .1       0   186.3    .045       0   217.3      .1       0
Bank Sta=186.3,217.3
XS Rating Curve= 0 ,0
Exp/Cntr=0.3,0.1

Type RM Length L Ch R = 1 ,18090   ,194.3,200.3,204.7
XS GIS Cut Line= 2
2006561.16542675304355.058893739 2006531.1838946304654.262347189
#Sta/Elev= 30
       0 1898.14    14.7 1896.67    21.3 1894.39    31.2  1887.9    60.7 1866.13
    67.5 1861.92    70.8 1860.67    77.4 1860.16    80.7  1858.8    87.7 1848.22
    90.7 1846.09    97.2 1844.93   113.6 1844.53   116.9  1844.8   120.61846.511
   132.6 1854.06   149.9 1862.48   162.6 1872.13     173 1882.04   176.3 1887.76
   179.6 1898.37   182.9 1905.13   196.1 1921.74   199.4 1927.88   202.7 1935.42
   212.6 1962.24   215.9 1967.29   248.8 1991.51   258.7 1996.98   300.7  2027.8
#Mann= 3 ,-1 , 0
       0      .1       0    87.7    .045       0   120.6      .1       0
Bank Sta=87.7,120.6
XS Rating Curve= 0 ,0
Exp/Cntr=0.3,0.1

Type RM Length L Ch R = 1 ,17890   ,237.8,254.3,270.9
XS GIS Cut Line= 2
2006385.97013615304316.3126274692006293.77910945304637.130043106
#Sta/Elev= 30
       0 1893.26      18 1891.49    25.6 1888.33    65.8 1862.31    72.6 1859.52
    82.9 1857.92    89.7 1848.83    95.3 1843.51   103.3 1840.25   126.4 1839.73
   131.7 1839.94   135.2 1841.59   147.7  1855.1     158  1864.8   168.2 1883.29
   178.4 1894.86   181.9 1899.81   188.7 1913.86   195.5 1926.76   198.9 1932.02
   212.6  1942.5   219.4 1949.52   229.6 1958.47   236.5 1962.51     274 1990.65
   284.3 1997.33   294.5 2005.89   304.7 2012.64   325.2  2028.3   333.8  2033.8
#Mann= 3 ,-1 , 0
       0      .1       0    95.3    .045       0   135.2      .1       0
Bank Sta=95.3,135.2
XS Rating Curve= 0 ,0
Exp/Cntr=0.3,0.1

Type RM Length L Ch R = 1 ,17635   ,70.9,79.2,90
XS GIS Cut Line= 3
 2006250.8162357304197.8240478962006103.28338136304325.745527266
 2006095.3793231 304407.53087065
#Sta/Elev= 30
       0 1885.83     9.5 1887.38    15.3 1887.45    26.9 1885.07    29.3 1884.18
      32  1882.9      42 1875.26    67.1 1860.02    71.1 1858.32    85.1  1854.3
   101.4 1846.56   115.3  1843.5   118.1 1842.34   122.1 1839.29   126.9 1836.59
   131.1 1835.57   136.2 1835.39   157.2 1835.72   162.2 1836.52   166.5 1839.28
   174.5 1848.04   183.2 1854.78   195.3 1866.49   200.1 1869.85   219.7 1879.37
   249.3 1890.48   255.9 1893.91   262.5 1896.63   269.1 1900.55   277.4  1904.2
#Mann= 3 ,-1 , 0
       0      .1       0   126.9    .045       0   162.2      .1       0
Bank Sta=126.9,162.2
XS Rating Curve= 0 ,0
Exp/Cntr(USF)=0,0
Exp/Cntr=0.3,0.1

Type RM Length L Ch R = 1 ,17556   ,126.8,108.8,87
XS GIS Cut Line= 3
2006232.48539923304174.2351748442006050.57405916304242.739761769
2006024.66896327304327.363075029
#Sta/Elev= 30
       0 1884.74    13.2 1886.49    25.9 1884.04    30.2 1882.63    37.2 1878.92
    47.7 1872.07    61.7 1863.88    72.2 1855.61      82 1849.89    87.1 1845.47
    98.5 1838.07     110 1828.78   114.3 1826.12   117.1  1825.8   126.4 1829.06
   143.1 1829.46   152.9  1831.4   159.9 1831.71   173.9 1833.84   188.9 1837.12
   191.4 1838.07   196.8 1841.21   209.8 1851.82   220.3    1862   225.5 1865.68
   231.1 1868.95   241.3 1873.23   251.8 1876.99   265.4 1880.21   282.9 1882.29
#Mann= 3 ,-1 , 0
       0      .1       0     110    .045       0   143.1      .1       0
Bank Sta=110,143.1
XS Rating Curve= 0 ,0
Exp/Cntr(USF)=0,0
Exp/Cntr=0.3,0.1

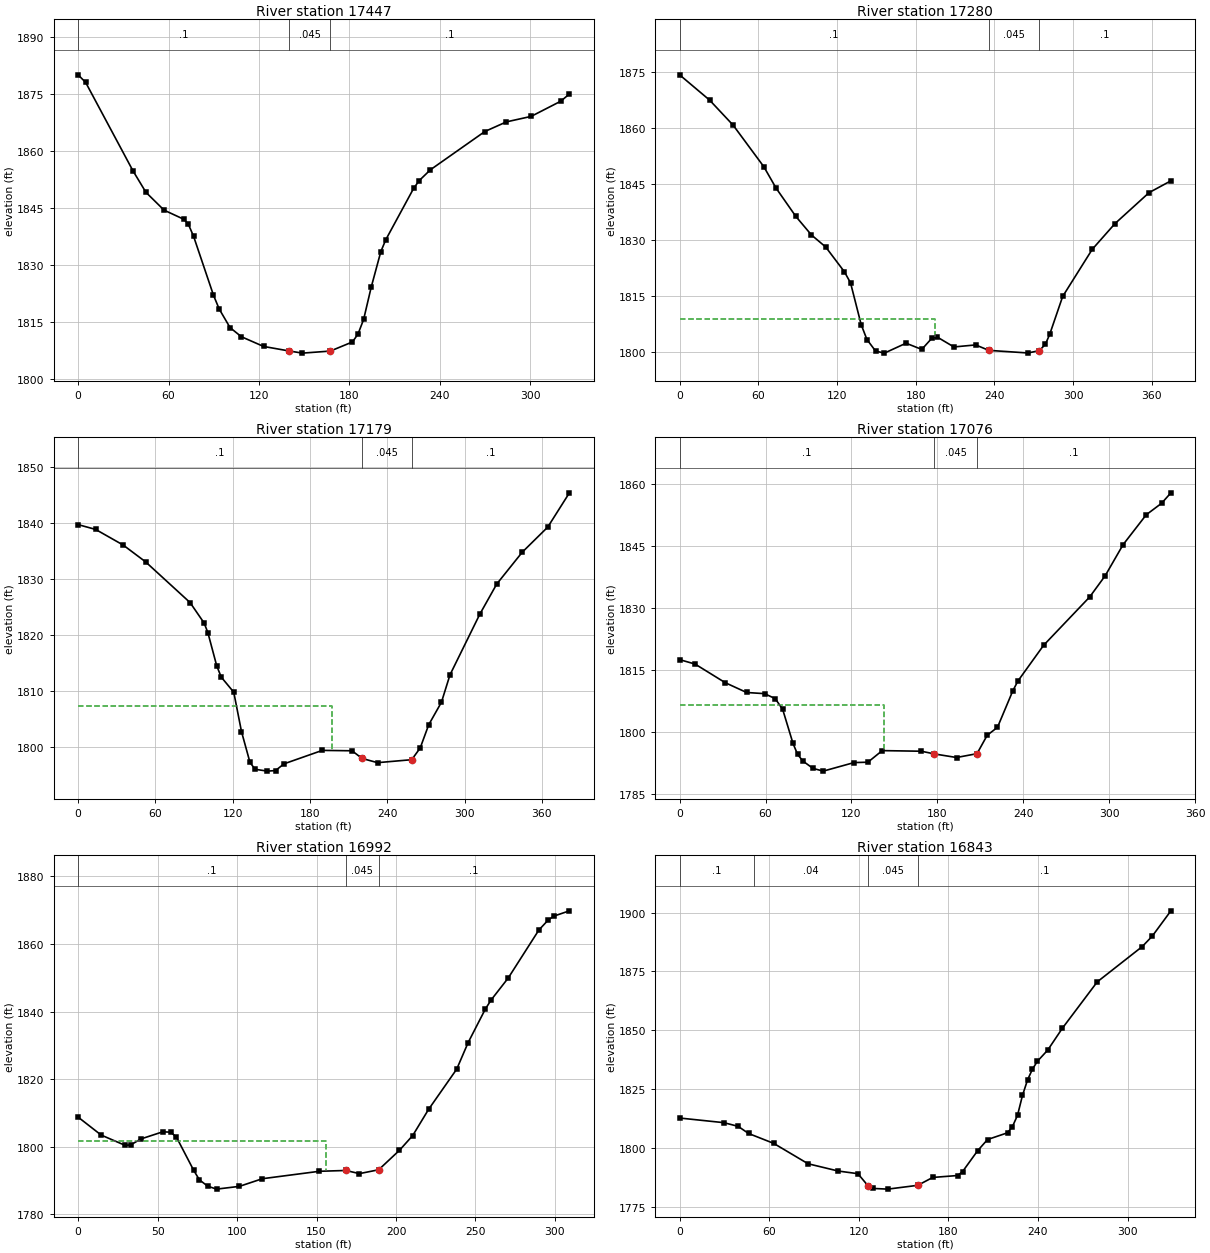
Type RM Length L Ch R = 1 ,17447   ,172.5,167.2,155.8
XS GIS Cut Line= 4
2006129.58919793 304050.707149992006069.18727486304092.942885306
2005991.48003849304244.0742820392005996.78998194304326.114291316
#Sta/Elev= 30
       0 1879.96       5 1877.97    36.4 1854.74      45  1849.1      57 1844.42
      70 1842.04      73 1840.83    76.6 1837.54    89.8 1822.07    93.6 1818.44
   100.8 1813.56   108.3 1811.17     123 1808.62   139.9 1807.43   148.8 1806.86
   167.3  1807.4     182  1809.8   185.7  1811.9   189.4 1815.72   194.4 1824.14
   200.8 1833.52   204.1 1836.65   222.6 1850.16   226.3 1852.19   233.7 1855.02
   269.8 1865.07   284.1  1867.6   300.5 1869.04   320.2 1873.04   325.9 1874.93
#Mann= 3 ,-1 , 0
       0      .1       0   139.9    .045       0   167.3      .1       0
Bank Sta=139.9,167.3
XS Rating Curve= 0 ,0
Exp/Cntr=0.3,0.1

Type RM Length L Ch R = 1 ,17280   ,108.2,101.4,92.8
XS GIS Cut Line= 3
2006001.73248033303926.9905169992005892.39369951304002.011056028
2005856.90535533304241.251445188
#Sta/Elev= 30
       0 1874.13    22.9 1867.37    40.9 1860.65    64.2  1849.6    73.6 1843.85
    88.6 1836.33   100.5 1831.38   111.4 1828.15   125.6 1821.56   130.3 1818.59
   138.4 1807.45   142.8 1803.46   149.4 1800.38   156.1 1799.83   172.6 1802.48
   184.6 1800.82   192.5  1803.9   195.9 1804.22   209.1 1801.48   225.7 1802.02
   235.7 1800.57   265.5 1799.87   274.2 1800.49   278.8 1802.18   282.1 1804.83
     292 1814.96   314.6 1827.57   331.9 1834.42   357.9 1842.69   374.5 1845.83
#Mann= 3 ,-1 , 0
       0      .1       0   235.7    .045       0   274.2      .1       0
#XS Ineff= 2 , 0
          194.56 1809.05
Permanent Ineff=
       F       F
Bank Sta=235.7,274.2
XS Rating Curve= 0 ,0
Exp/Cntr=0.3,0.1

Type RM Length L Ch R = 1 ,17179   ,111.8,102.6,94.3
XS GIS Cut Line= 3
 2005876.7532773303961.9165876662005761.99633285  303999.5901988
2005791.68383288304258.444365457
#Sta/Elev= 30
       0 1839.76    13.6  1838.9      35 1836.11    52.4 1833.11    86.9 1825.85
    97.8  1822.2   100.7  1820.5   107.6 1814.55   111.1 1812.55   120.8 1809.86
   126.8 1802.84   133.4 1797.32   137.4 1796.11   146.9 1795.78   153.2 1795.88
   159.8 1797.08   189.5 1799.48   212.6 1799.41   220.4 1798.04   232.4 1797.29
   258.9 1797.82   265.5 1799.91   272.1 1804.05     282 1808.08   288.6 1812.95
   311.7 1823.75   324.9 1829.16   344.7 1834.84   364.5 1839.32   381.3 1845.43
#Mann= 3 ,-1 , 0
       0      .1       0   220.4    .045       0   258.9      .1       0
#XS Ineff= 2 , 0
          197.17 1807.35
Permanent Ineff=
       F       F
Bank Sta=220.4,258.9
XS Rating Curve= 0 ,0
Exp/Cntr(USF)=0,0
Exp/Cntr=0.3,0.1

Type RM Length L Ch R = 1 ,17076   ,81.9,84.2,80.3
XS GIS Cut Line= 2
2005604.59667425303982.5370348952005741.87417078304296.931433458
#Sta/Elev= 30
       0 1817.43    10.8 1816.36    31.9 1811.84    46.8 1809.47    59.3 1809.19
    66.8 1807.98      72 1805.36    79.2 1797.13    82.4 1794.48      86 1792.89
    93.1 1791.09   100.3 1790.42   121.8 1792.49   131.5 1792.58   141.5 1795.39
   168.9 1795.24     178 1794.58   193.4 1793.72   207.7 1794.65   214.8  1799.1
     222 1801.04   232.7 1809.88   236.3 1812.27   254.2  1820.9   286.4 1832.62
   297.2 1837.75   309.7 1845.28   325.9 1852.53   336.6 1855.31   343.1 1857.84
#Mann= 3 ,-1 , 0
       0      .1       0     178    .045       0   207.7      .1       0
#XS Ineff= 2 , 0
          142.82 1806.54
Permanent Ineff=
       F       F
Bank Sta=178,207.7
XS Rating Curve= 0 ,0
Exp/Cntr=0.3,0.1

Type RM Length L Ch R = 1 ,16992   ,147.2,149.2,153.9
XS GIS Cut Line= 2
2005542.63828757304040.9766513052005669.57325745304322.824094639
#Sta/Elev= 30
       0 1808.75    14.5 1803.44    29.5 1800.41    33.1 1800.52    39.4 1802.27
    53.2 1804.39    58.3  1804.3    61.9 1802.79    72.7 1793.02    76.3  1790.2
    81.5 1788.32    87.1 1787.44   101.5 1788.26   115.9 1790.52   151.8 1792.72
   168.4 1792.96     177 1792.03   189.1 1793.17   202.2 1798.94   210.5 1803.29
   220.5 1811.04   238.2 1822.95   245.4 1830.82   256.2 1840.71   259.8 1843.39
   270.6 1849.91   289.9 1864.12   295.8 1867.09   299.4 1868.24   309.1 1869.79
#Mann= 3 ,-1 , 0
       0      .1       0   168.4    .045       0   189.1      .1       0
#XS Ineff= 2 , 0
          156.15 1801.69
Permanent Ineff=
       F       F
Bank Sta=168.4,189.1
XS Rating Curve= 0 ,0
Exp/Cntr(USF)=0,0
Exp/Cntr=0.3,0.1

Type RM Length L Ch R = 1 ,16843   ,72.6,76.5,83.1
XS GIS Cut Line= 3
2005468.76716623304058.2707543372005457.48244396304136.395754352
2005504.35744396304382.055476591
#Sta/Elev= 30
       0 1812.66    29.6 1810.69    39.2 1809.12    46.2 1806.08      63 1801.88
      86 1793.21   106.2 1790.11   119.4 1788.98   126.1 1783.88   129.4 1782.71
   139.4 1782.41   159.5 1784.03   169.5 1787.38   186.2  1788.2   189.5 1789.88
   199.6 1798.77   206.2  1803.5   219.6 1806.38   222.9 1809.03   226.3 1813.84
   229.6 1822.26     233 1828.88   236.3 1833.47   239.6 1836.81   246.5 1841.55
   256.3 1850.84   279.7  1870.6   309.8  1885.6   316.5 1890.03     329 1900.81
#Mann= 4 ,-1 , 0
       0      .1       0      50     .04       0   126.1    .045       0
   159.5      .1       0
Bank Sta=126.1,159.5
XS Rating Curve= 0 ,0
Exp/Cntr(USF)=0,0
Exp/Cntr=0.3,0.1