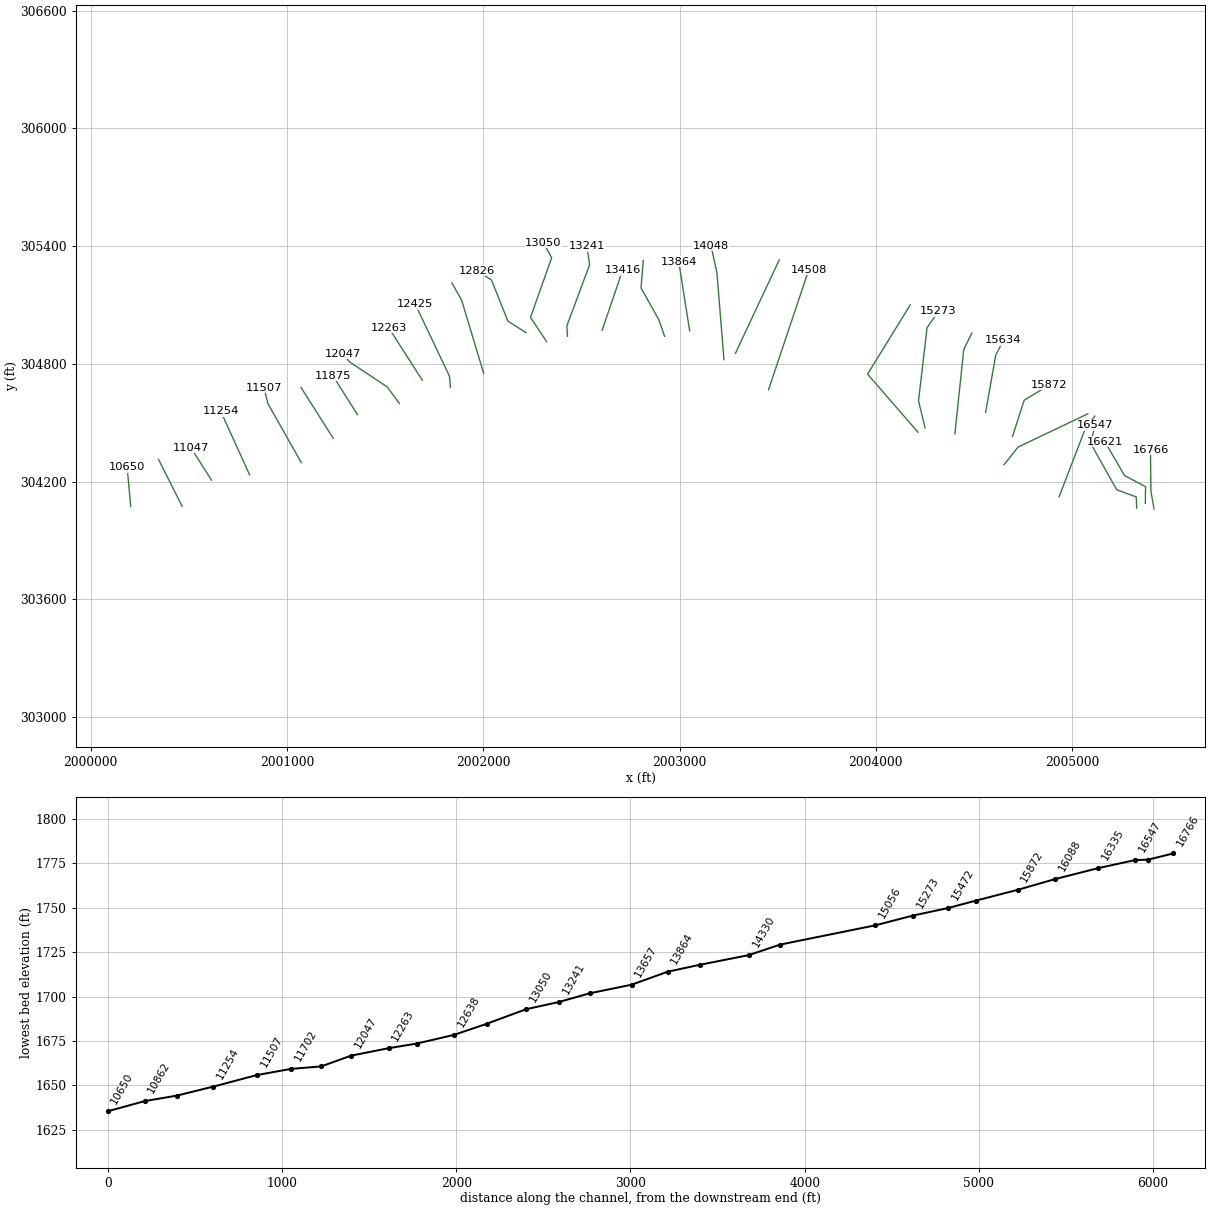
HEC-RAS study MEADOWCK_A.prj: MEADOWCK_A

--- MEADOWCK_A.g01 (geometry) --- (continued)

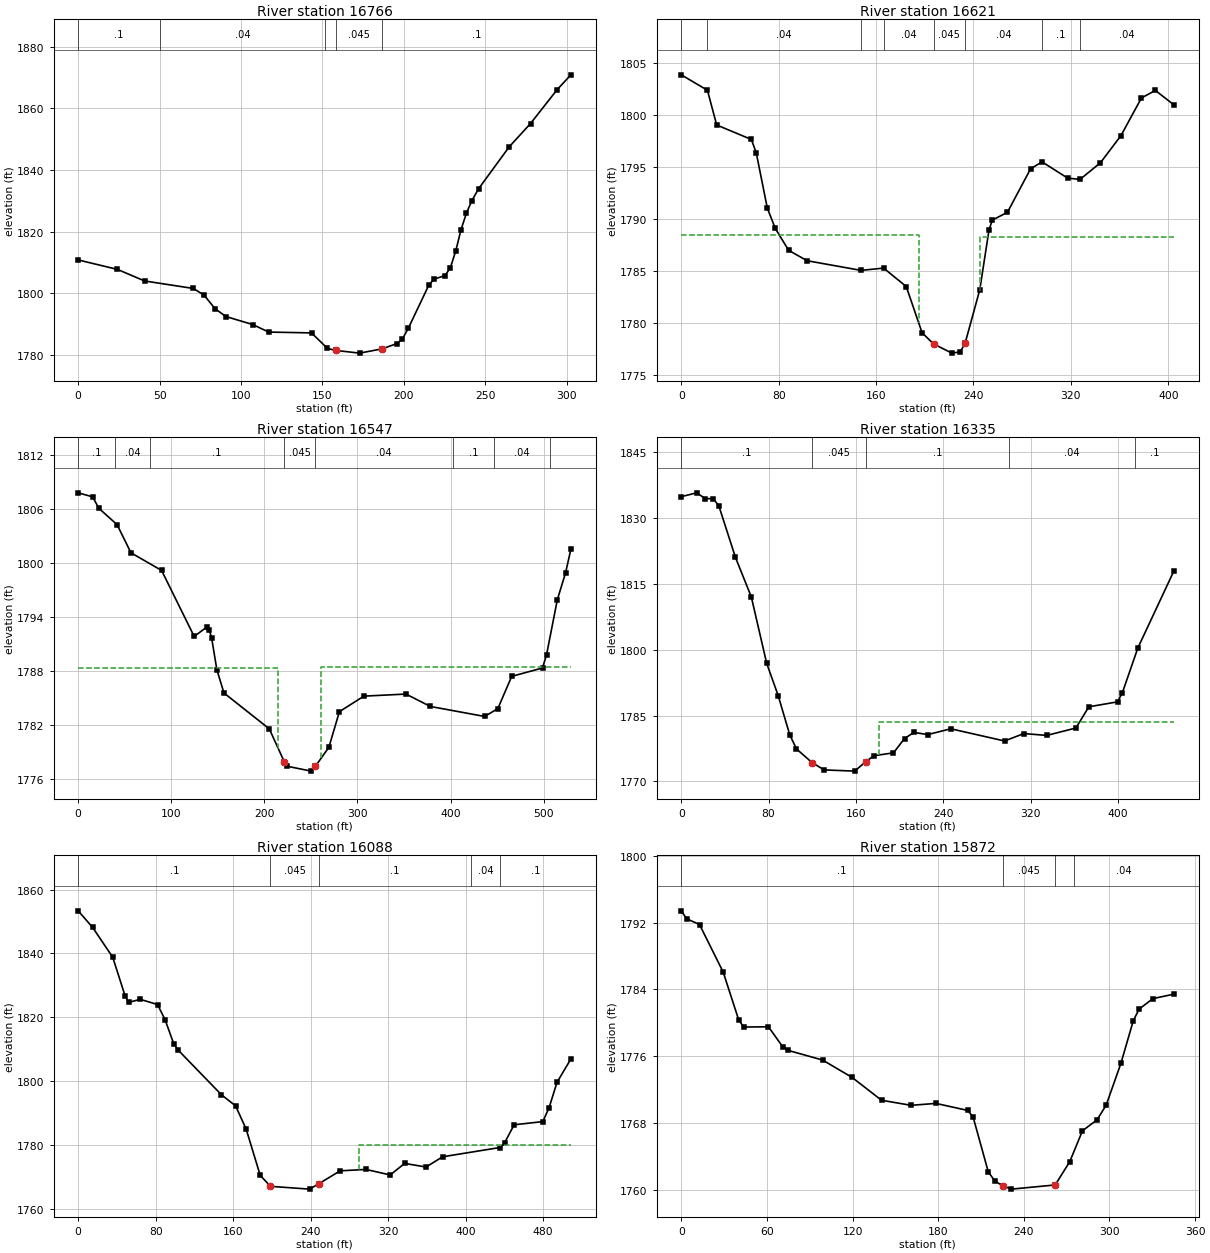
Type RM Length L Ch R = 1 ,16766   ,115.1,145.6,153.3
XS GIS Cut Line= 3
2005417.20313435304060.5248117892005401.16546026304150.783307118
2005398.97383257304361.704949567
#Sta/Elev= 30
       0 1810.85    24.1 1807.78    40.8 1804.03    70.8 1801.59    77.4 1799.39
    84.1    1795    90.8 1792.48   107.2 1789.89     117 1787.45   143.3 1787.18
   153.1 1782.14   158.31781.493   172.8 1780.62   186.61781.999   195.8 1783.72
   199.1  1785.2   202.8 1788.75   215.5 1802.86   218.7 1804.65   225.3 1805.78
   228.6 1808.35   231.9 1813.83   235.1 1820.65   238.4 1825.97   241.7 1830.03
   245.9 1833.94   264.7 1847.54   277.8  1855.1   294.2 1866.13   302.6  1870.9
#Mann= 5 ,-1 , 0
       0      .1       0      50     .04       0  151.67      .1       0
   158.3    .045       0   186.6      .1       0
Bank Sta=158.3,186.6
XS Rating Curve= 0 ,0
Exp/Cntr(USF)=0,0
Exp/Cntr=0.5,0.3

Type RM Length L Ch R = 1 ,16621   ,89.9,74,73.1
XS GIS Cut Line= 4
 2005372.8393499304089.052081064  2005373.678528304174.187083142
2005266.85021471304230.9374724242005167.04434563304402.648029654
#Sta/Elev= 30
       0 1803.85    21.5 1802.37    29.1 1799.03    57.6 1797.64    61.6 1796.36
    70.7 1791.04    77.2  1789.1    88.2 1786.99   103.3 1785.99   147.7 1785.06
   166.2 1785.28   184.8 1783.51   197.8 1779.07   207.31777.983   222.4 1777.11
   229.1 1777.23   233.11778.038   245.2  1783.2   252.8 1788.96   255.5 1789.89
   267.9 1790.64   286.9 1794.81   296.3 1795.49   317.3 1793.93   327.5  1793.8
   344.3  1795.4   361.1    1798     378 1801.63   389.4 1802.35   404.7 1800.96
#Mann= 8 ,-1 , 0
       0      .1       0    21.5     .04       0   147.7      .1       0
   166.2     .04       0   207.3    .045       0   233.1     .04       0
   296.3      .1       0   327.5     .04       0
#XS Ineff= 2 , 0
             195  1788.5     245          1788.3
Permanent Ineff=
       F       F
Bank Sta=207.3,233.1
XS Rating Curve= 0 ,0
Exp/Cntr(USF)=0,0
Exp/Cntr=0.5,0.3

Type RM Length L Ch R = 1 ,16547   ,240.1,211.4,191
XS GIS Cut Line= 5
2005328.54897997304065.4483943592005326.38866657304122.106875371
2005227.09377891304158.459411614 2005092.7577837304397.397874307
2005117.61493472304486.763965384
#Sta/Elev= 30
       0 1807.83    15.6 1807.38    22.1 1806.12    41.8 1804.29    56.7 1801.16
    89.6  1799.2   124.6 1791.86   138.3 1792.91   140.8 1792.61   143.4 1791.66
     149 1788.15   156.6 1785.57   205.3 1781.58   221.31777.945   224.6 1777.42
   250.4 1776.88   254.71777.399   269.3 1779.53   280.6 1783.49   306.9 1785.22
   352.1 1785.45   378.4 1784.07   436.6 1782.96   450.8 1783.83   465.7 1787.42
   498.8 1788.35   503.2 1789.85   514.7 1795.94   523.6 1798.95   529.3 1801.57
#Mann= 8 ,-1 , 0
       0      .1       0      40     .04       0    76.7      .1       0
   221.3    .045       0   254.7     .04       0  402.44      .1       0
  446.55     .04       0  506.55      .1       0
#XS Ineff= 2 , 0
             215  1788.3     261          1788.5
Permanent Ineff=
       F       F
Bank Sta=221.3,254.7
XS Rating Curve= 0 ,0
Exp/Cntr(USF)=0,0
Exp/Cntr=0.5,0.3

Type RM Length L Ch R = 1 ,16335   ,273,247.5,221.5
XS GIS Cut Line= 3
 2004933.6375023304122.7813361262005061.03111342304454.506537486
2005115.02872444304533.781197916
#Sta/Elev= 30
       0  1834.9    14.1 1835.78      22 1834.47    29.3 1834.42    34.4 1832.84
    49.6  1821.1    64.2 1812.04    78.2 1796.97    88.8 1789.55    99.3 1780.69
   105.5 1777.42   119.91774.275   130.9 1772.63   158.8 1772.35   169.21774.537
   176.5 1775.86   194.4 1776.52   204.5 1779.78   213.1 1781.17   225.8 1780.68
   246.9    1782   296.1 1779.22   313.8 1780.91   334.8 1780.49   361.5 1782.18
   373.3 1787.01   399.6 1788.14     404  1790.2   418.2 1800.41   451.3 1818.01
#Mann= 5 ,-1 , 0
       0      .1       0   119.9    .045       0   169.2      .1       0
     300     .04       0  415.35      .1       0
#XS Ineff= 2 , 0
                          181.18         1783.46
Permanent Ineff=
       F       F
Bank Sta=119.9,169.2
XS Rating Curve= 0 ,0
Exp/Cntr(USF)=0,0
Exp/Cntr=0.3,0.1

Type RM Length L Ch R = 1 ,16088   ,220.7,215.7,221.8
XS GIS Cut Line= 3
2004652.78939976304286.005793882 2004724.6705556304376.138306091
2005079.69213422304545.486165615
#Sta/Elev= 30
       0 1853.33    14.9 1848.14    35.7 1838.77    48.3  1826.8      52 1824.65
      64 1825.61    81.9 1823.99    89.7 1819.22    98.7 1811.65   102.9  1809.8
   147.9 1795.72   162.5 1792.24   173.4 1784.95   187.9 1770.48   198.51767.048
   238.8 1766.17   248.5 1767.88   270.4  1771.9     297 1772.34   322.1 1770.61
     337 1774.23     359 1773.09   376.2  1776.3   435.3  1779.2   440.2 1780.71
     450 1786.32   479.6 1787.32     486 1791.62   494.3 1799.64   508.6 1806.95
#Mann= 5 ,-1 , 0
       0      .1       0   198.5    .045       0   248.5      .1       0
  405.29     .04       0  435.29      .1       0
#XS Ineff= 2 , 0
                             290            1780
Permanent Ineff=
       F       F
Bank Sta=198.5,248.5
XS Rating Curve= 0 ,0
Exp/Cntr=0.3,0.1

Type RM Length L Ch R = 1 ,15872   ,220.6,238.7,269.6
XS GIS Cut Line= 3
2004695.91305483304429.7103260382004755.71206958 304615.17571945
2004884.41984876304692.801016403
#Sta/Elev= 30
       0 1793.41     3.8 1792.46    12.8 1791.77    29.4 1786.07    40.3 1780.33
    43.8  1779.5    61.1 1779.53      71 1777.16    74.8 1776.71      99 1775.55
   119.7 1773.47   140.3 1770.74     161 1770.13   178.4 1770.36   200.7 1769.52
   204.5 1768.72   215.1 1762.17   219.8 1761.05   225.2 1760.51   231.3  1760.1
     262  1760.6   272.2 1763.39   281.1 1767.09   291.3 1768.39   297.7 1770.16
     308 1775.14   316.7 1780.26   320.8 1781.65   330.4  1782.9   345.2 1783.44
#Mann= 4 ,-1 , 0
       0      .1       0   225.2    .045       0     262      .1       0
  274.87     .04       0
Bank Sta=225.2,262
XS Rating Curve= 0 ,0
Exp/Cntr=0.3,0.1

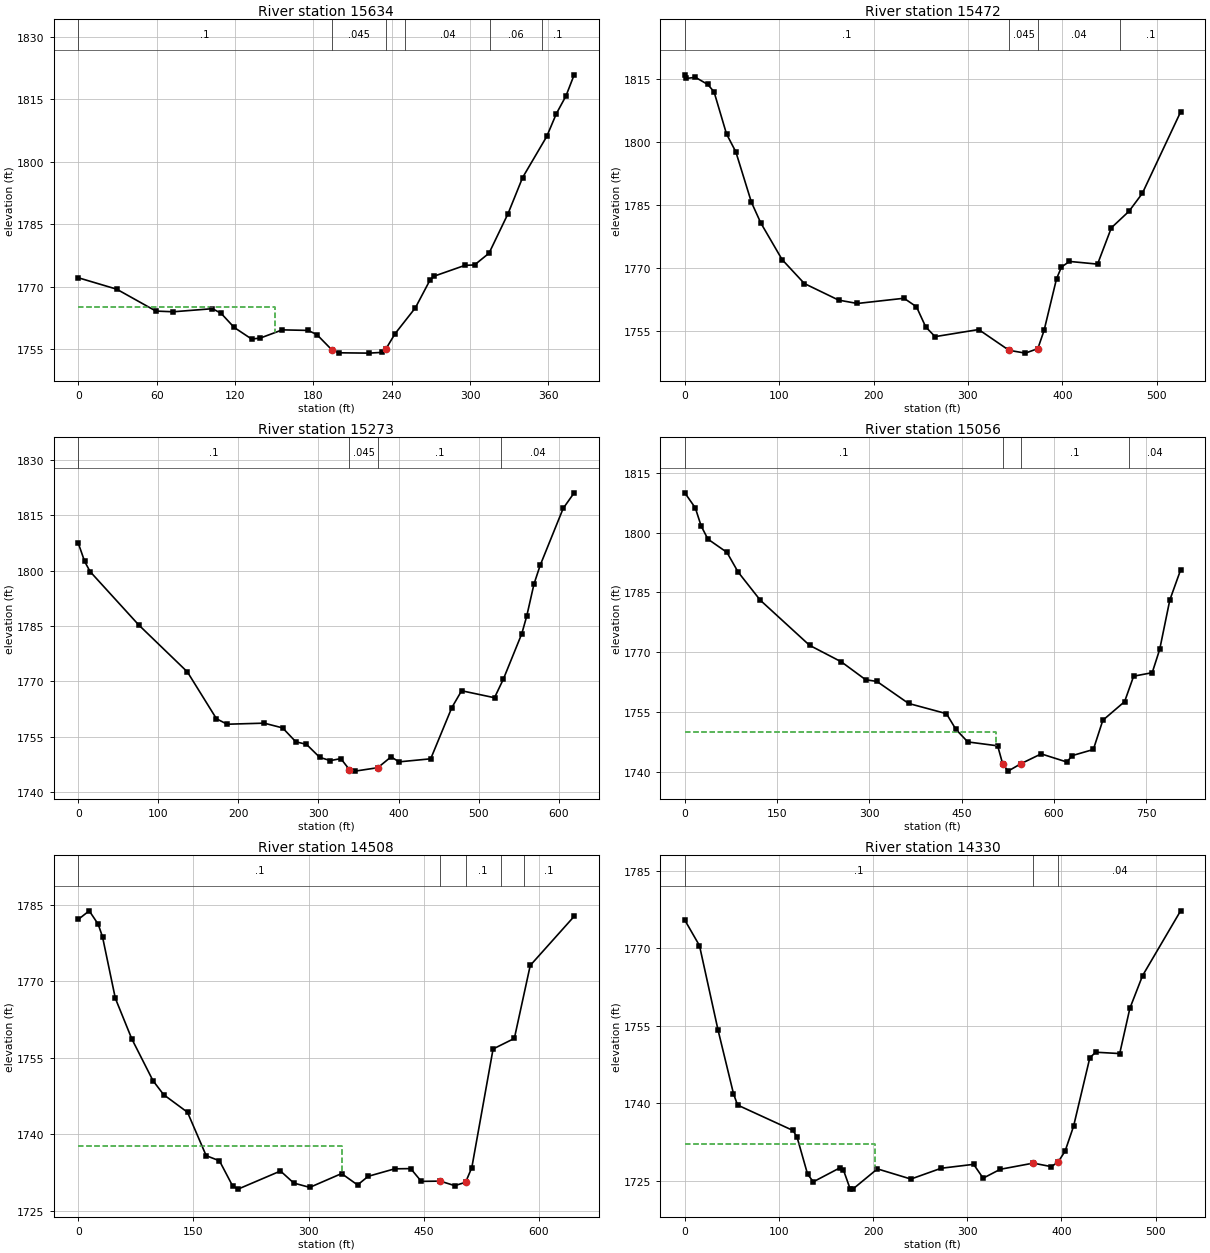
Type RM Length L Ch R = 1 ,15634   ,159.9,161.5,162.7
XS GIS Cut Line= 3
 2004559.2817315304554.0426279942004610.92162202304844.824642868
2004649.40881881304919.936897197
#Sta/Elev= 30
       0 1772.13    29.4 1769.39    59.4 1764.14    72.7 1763.97   102.7 1764.71
   109.3 1763.61   119.3 1760.22   132.7 1757.43   139.3 1757.66   156.2 1759.63
     176  1759.5   182.7 1758.49   194.11754.851   199.3 1754.13   222.6 1754.05
   232.7 1754.23   235.4 1754.99   242.6 1758.73   258.1 1764.92   269.4 1771.63
   272.6 1772.53     296  1775.1   303.4 1775.21   314.5 1778.02   329.1 1787.54
   340.2 1796.16   358.7 1806.03   366.1 1811.52   373.4 1815.73   379.7 1820.82
#Mann= 6 ,-1 , 0
       0      .1       0   194.1    .045       0   235.4      .1       0
     250     .04       0  315.33     .06       0  355.33      .1       0
#XS Ineff= 2 , 0
           150.6    1765
Permanent Ineff=
       F       F
Bank Sta=194.1,235.4
XS Rating Curve= 0 ,0
Exp/Cntr=0.3,0.1

Type RM Length L Ch R = 1 ,15472   ,199.6,199.4,199
XS GIS Cut Line= 3
 2004402.6358445304443.8403395132004447.71951789304872.802146433
2004489.01991726304957.306718985
#Sta/Elev= 30
       0 1816.02     1.3 1815.15    11.2 1815.43    24.4 1813.72      31 1811.97
    44.2 1801.96    54.1 1797.69    70.6 1785.71    80.5  1780.8   103.1 1772.08
   126.7 1766.38     163 1762.44   182.8 1761.64   232.3 1762.88   245.5 1760.85
   255.3 1756.06   265.2 1753.75   311.4 1755.44   343.61750.496   360.9 1749.83
   374.1 1750.91   380.7 1755.22   393.9 1767.51   399.1 1770.29   407.6 1771.64
   437.4    1771     452 1779.64   470.7 1783.57   484.8 1787.82   525.4  1807.2
#Mann= 4 ,-1 , 0
       0      .1       0   343.6    .045       0   374.1     .04       0
  461.32      .1       0
Bank Sta=343.6,374.1
XS Rating Curve= 0 ,0
Exp/Cntr=0.3,0.1

Type RM Length L Ch R = 1 ,15273   ,227.3,216.5,205.4
XS GIS Cut Line= 4
2004250.83484023304473.5696747472004217.37140521304611.678779827
2004260.99883595 304984.765021392004319.06108274305068.208897297
#Sta/Elev= 30
       0 1807.36     7.9 1802.45    14.7 1799.71    75.4 1785.26   136.2 1772.53
   172.6 1759.82   185.9 1758.35   232.1 1758.64   255.2 1757.35   271.7 1753.59
     285  1752.9   301.5 1749.38   314.7 1748.49   327.9 1749.03   338.61746.063
   345.7 1745.64   374.1 1746.57   390.7 1749.51   400.6 1748.15   440.2 1748.98
   466.6 1762.86   478.8 1767.42   519.9 1765.53     531 1770.59     554 1782.89
   560.1  1787.6   569.2 1796.32   576.9 1801.38   605.7 1816.84   619.4 1821.05
#Mann= 4 ,-1 , 0
       0      .1       0   338.6    .045       0   374.1      .1       0
  527.73     .04       0
Bank Sta=338.6,374.1
XS Rating Curve= 0 ,0
Exp/Cntr=0.3,0.1

Type RM Length L Ch R = 1 ,15056   ,538.4,547.8,551.4
XS GIS Cut Line= 3
2004214.46594562304451.9439126972003957.82532591304747.854811057
2004175.27324259305100.719394401
#Sta/Elev= 30
       0 1809.97    17.1 1806.19    26.6 1801.64    37.6 1798.35    68.5 1795.03
    86.6 1790.11   122.7 1783.03   202.8 1771.71   254.5 1767.56   294.1 1763.06
   312.4 1762.64   363.8 1757.12   425.4 1754.55   440.8 1750.61   460.1 1747.46
   508.7 1746.48   516.8 1741.98   525.6 1740.13   546.31741.974   579.5 1744.46
   621.3 1742.41   629.6 1744.01   664.3 1745.56   679.7 1752.89   715.1 1757.57
   729.8 1763.96     760 1764.83   772.2  1770.7   788.6 1783.06   806.2 1790.64
#Mann= 4 ,-1 , 0
       0      .1       0   516.8    .045       0   546.3      .1       0
   721.7     .04       0
#XS Ineff= 2 , 0
             506    1750
Permanent Ineff=
       F       F
Bank Sta=516.8,546.3
XS Rating Curve= 0 ,0
Exp/Cntr(USF)=0,0
Exp/Cntr=0.3,0.1

Type RM Length L Ch R = 1 ,14508   ,180.1,178.4,175.8
XS GIS Cut Line= 2
2003453.26942673304667.9273571642003658.56532858 305280.20957195
#Sta/Elev= 30
       0  1782.1    14.2 1783.77    25.9 1781.13    31.5 1778.67    48.2 1766.63
    69.6 1758.69    97.2  1750.5   111.1 1747.75   142.2  1744.3   166.5  1735.8
   183.8 1734.79   200.9 1729.88     208 1729.24   263.3 1732.79   280.6 1730.43
   301.4 1729.58   342.9 1732.29   363.7 1730.06   377.5 1731.75   412.1 1733.22
   432.9 1733.26   446.7 1730.76   471.4 1730.81   490.3 1729.92   504.41730.584
   512.5 1733.46   540.2  1756.7   567.9 1758.77   588.6 1773.07   645.8 1782.69
#Mann= 5 ,-1 , 0
       0      .1       0   471.4    .045       0   504.4      .1       0
     550     .04       0     580      .1       0
#XS Ineff= 2 , 0
          343.53 1737.78
Permanent Ineff=
       F       F
Bank Sta=471.4,504.4
XS Rating Curve= 0 ,0
Exp/Cntr=0.3,0.1

Type RM Length L Ch R = 1 ,14330   ,265.3,281.7,288.9
XS GIS Cut Line= 2
2003284.77392284304853.7902908642003508.12833318305330.545903783
#Sta/Elev= 30
       0 1775.43    15.6 1770.48    35.3 1754.14    51.7 1741.83      56 1739.63
   114.9  1734.7   119.2 1733.42   130.4 1726.23   136.5 1724.77   164.7 1727.47
   168.3 1727.13   175.5 1723.43   178.4 1723.35   204.5 1727.27   240.1  1725.3
   272.2 1727.39   306.7 1728.15   316.8 1725.47     335 1727.19     3701728.382
   389.3  1727.7   396.5 1728.63   403.8 1730.69   412.8 1735.51   430.1 1748.79
   436.4 1749.85   461.8 1749.59   472.6 1758.35   486.1 1764.68   526.5 1777.22
#Mann= 3 ,-1 , 0
       0      .1       0     370    .045       0   396.5     .04       0
#XS Ineff= 2 , 0
             202    1732
Permanent Ineff=
       F       F
Bank Sta=370,396.5
XS Rating Curve= 0 ,0
Exp/Cntr(USF)=0,0
Exp/Cntr=0.3,0.1

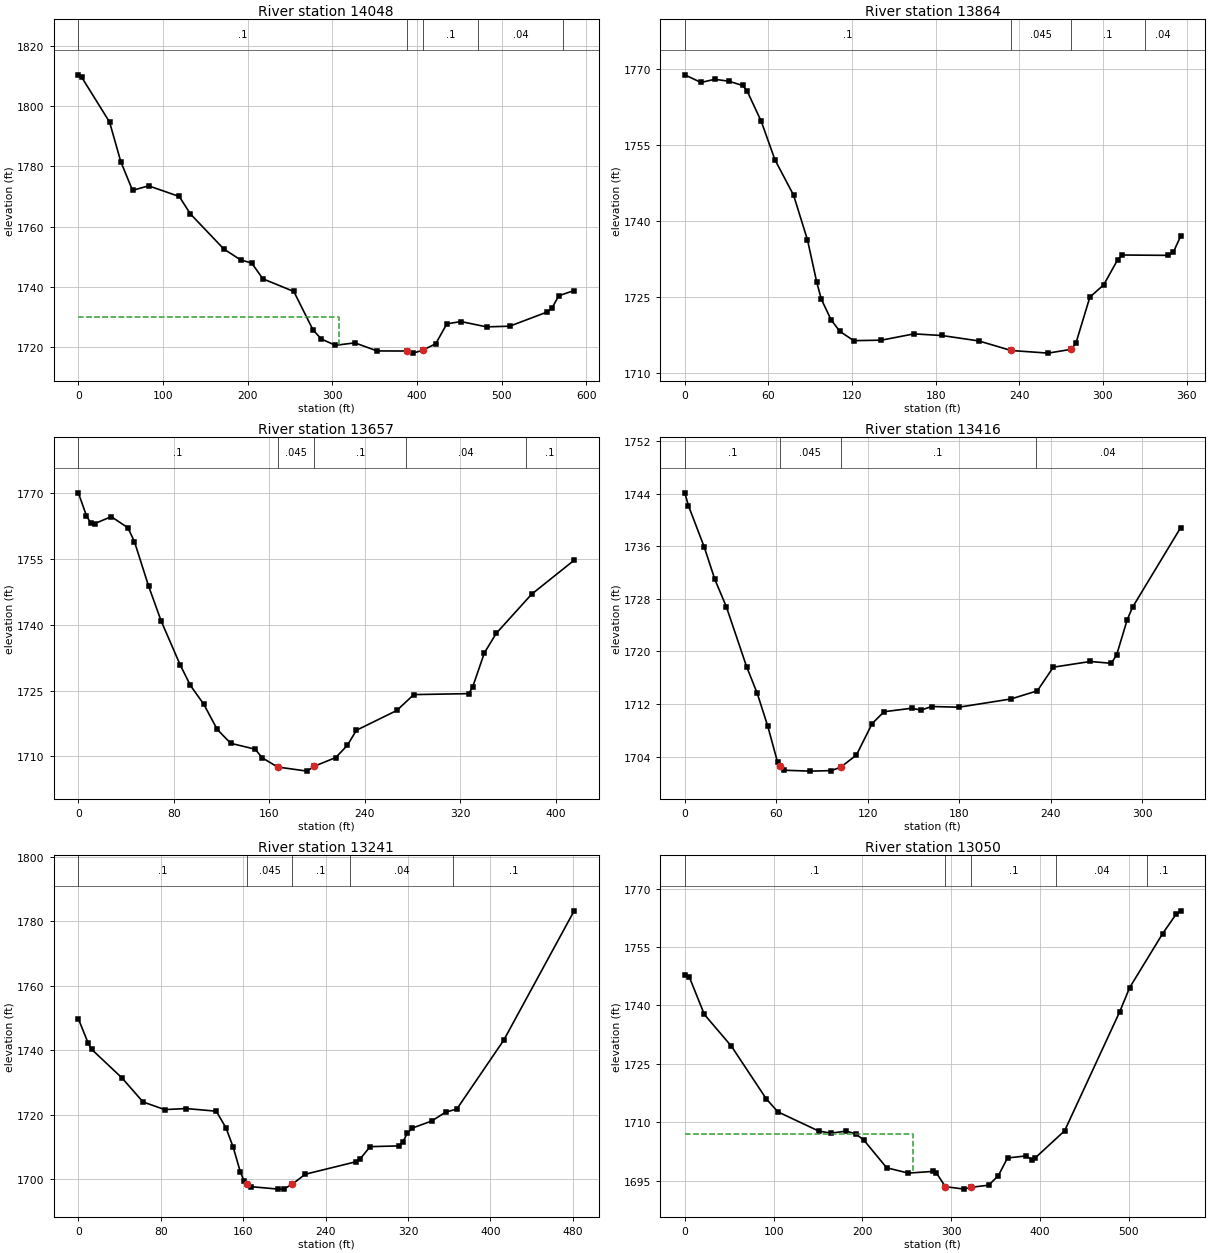
Type RM Length L Ch R = 1 ,14048   ,179.9,184.7,187.9
XS GIS Cut Line= 3
     2003226.426      304821.7312003190.69782791305262.343136154
2003160.55591135 305402.68033218
#Sta/Elev= 30
       0 1810.51       4 1809.69    36.9 1794.78    50.1 1781.65      64 1772.06
      83 1773.56   119.2 1770.02   132.4  1764.2   171.9 1752.51   191.6 1748.93
   204.8 1747.86   217.9 1742.62   254.5  1738.4   277.2 1725.59   287.1 1722.56
   303.6 1720.48   326.6  1721.3   352.9 1718.61   388.4 1718.58   395.7 1717.88
   406.7 1718.86   422.1 1720.99   435.2 1727.62   451.9 1728.39   482.1 1726.62
   509.4 1726.84   553.6 1731.55   559.3 1732.83   567.4 1736.97   585.6 1738.71
#Mann= 5 ,-1 , 0
       0      .1       0   388.4    .045       0   406.7      .1       0
  472.06     .04       0  572.06      .1       0
#XS Ineff= 2 , 0
          307.51 1730.05
Permanent Ineff=
       F       F
Bank Sta=388.4,406.7
XS Rating Curve= 0 ,0
Exp/Cntr=0.3,0.1

Type RM Length L Ch R = 1 ,13864   ,192.7,207,216.7
XS GIS Cut Line= 2
2003051.64282169304968.5071868682002996.25900177305319.844071193
#Sta/Elev= 30
       0 1768.92    11.6 1767.41    21.5 1768.04    31.5 1767.66    41.5 1766.82
    44.7 1765.73    54.8 1759.76    64.7 1752.13      78 1745.19      88 1736.35
    94.6 1728.05    97.9 1724.66   104.9 1720.58   111.2 1718.28   121.2 1716.44
   141.1 1716.54   164.4 1717.78   184.3 1717.46   210.9 1716.39   234.1  1714.5
   260.7 1713.98   277.3 1714.74   280.6 1715.97   290.6 1725.04   300.5 1727.45
   310.5  1732.4   313.8 1733.35     347 1733.28   350.4 1733.85   355.7 1737.06
#Mann= 4 ,-1 , 0
       0      .1       0   234.1    .045       0   277.3      .1       0
     330     .04       0
Bank Sta=234.1,277.3
XS Rating Curve= 0 ,0
Exp/Cntr=0.3,0.1

Type RM Length L Ch R = 1 ,13657   ,262.6,240.9,215.3
XS GIS Cut Line= 4
 2002923.8544098304940.7502526782002894.18492048305026.067507366
2002803.86543751305187.1353146042002815.40836013305327.168925714
#Sta/Elev= 30
       0 1769.97     6.8 1764.76    10.2  1763.2    13.7 1762.96    27.6 1764.55
    41.5 1762.03      47 1758.88    58.9 1748.74    69.3 1740.89    85.2 1730.91
    93.9 1726.17   105.2 1721.84   116.4 1716.14   127.7 1712.99   148.2 1711.65
   154.1 1709.68     1671707.596   191.7 1706.66   197.71707.765   215.7 1709.75
   225.4 1712.51     233 1715.95   266.9 1720.46   281.1 1724.07   327.2 1724.29
   330.5 1725.85   340.3 1733.58   350.2    1738   379.8 1746.89   415.5 1754.64
#Mann= 5 ,-1 , 0
       0      .1       0     167    .045       0   197.7      .1       0
  274.99     .04       0  374.99      .1       0
Bank Sta=167,197.7
XS Rating Curve= 0 ,0
Exp/Cntr=0.3,0.1

Type RM Length L Ch R = 1 ,13416   ,175,174.6,173.5
XS GIS Cut Line= 2
 2002605.8191997304971.1060677062002710.49548033305278.779310915
#Sta/Elev= 30
       0 1744.12     2.4 1742.16    12.8 1735.84    19.7 1730.95    27.2 1726.82
    40.5  1717.7    47.5 1713.62    54.4 1708.63    60.8 1703.17    62.4 1702.53
    64.8 1701.95    82.1 1701.81      96 1701.89   102.1 1702.39   112.5 1704.26
   122.8 1709.04   130.6 1710.84   148.7 1711.37   154.9 1711.09   161.8 1711.63
   179.7 1711.53   213.8 1712.78   231.1 1714.02   241.5 1717.61   265.8 1718.48
   279.6  1718.2   283.1 1719.52     290 1724.83   293.5 1726.73     325 1738.82
#Mann= 4 ,-1 , 0
       0      .1       0    62.4    .045       0   102.1      .1       0
     230     .04       0
Bank Sta=62.4,102.1
XS Rating Curve= 0 ,0
Exp/Cntr=0.3,0.1

Type RM Length L Ch R = 1 ,13241   ,191.6,191.2,191.7
XS GIS Cut Line= 4
2002429.42328057304940.7941236872002426.30093647304994.460482262
2002542.01899983 305305.093668152002527.88933715305400.201883406
#Sta/Elev= 30
       0 1749.85     9.6  1742.2    12.9 1740.34    42.5 1731.42    62.8 1724.01
    83.8 1721.64   104.8 1721.96   133.9 1721.14   143.3    1716   150.3 1710.03
   157.3 1702.29   161.1 1699.35   163.61698.435   167.8 1697.72   194.3 1696.96
   199.7    1697   207.91698.542   220.3 1701.58   269.3 1705.43   273.4 1706.25
   283.3 1710.14   311.3 1710.37   314.9 1711.44   319.3 1714.29   324.4 1715.92
   342.9 1718.07   356.9 1720.89   367.4 1721.77   413.1 1743.21   481.4 1783.31
#Mann= 5 ,-1 , 0
       0      .1       0   163.6    .045       0   207.9      .1       0
  263.76     .04       0  363.76      .1       0
Bank Sta=163.6,207.9
XS Rating Curve= 0 ,0
Exp/Cntr=0.3,0.1

Type RM Length L Ch R = 1 ,13050   ,202.5,223.8,238.2
XS GIS Cut Line= 4
2002322.95825225304913.2718209142002240.94750578305036.795294584
2002348.75815276 305340.684108132002306.90825366305417.519647804
#Sta/Elev= 30
       0 1747.84     5.2 1747.22      22 1737.69    52.5 1729.52    91.8 1715.98
   104.8 1712.67   150.6 1707.75   164.5 1707.19   181.9 1707.73   192.4    1707
   201.4 1705.46   227.3  1698.3   251.6 1696.94   279.4 1697.37   282.9 1697.09
   293.3 1693.46   314.5 1692.82   322.2 1693.29   342.1 1693.83     353 1696.29
   363.3 1700.82   383.9 1701.34   390.8 1700.41   394.2 1700.78   427.6  1707.8
   489.6 1738.36   500.8 1744.57     538 1758.47   553.1 1763.43   558.2  1764.3
#Mann= 5 ,-1 , 0
       0      .1       0   293.3    .045       0   322.2      .1       0
  418.27     .04       0  520.72      .1       0
#XS Ineff= 2 , 0
             257    1707
Permanent Ineff=
       F       F
Bank Sta=293.3,322.2
XS Rating Curve= 0 ,0
Exp/Cntr=0.3,0.1

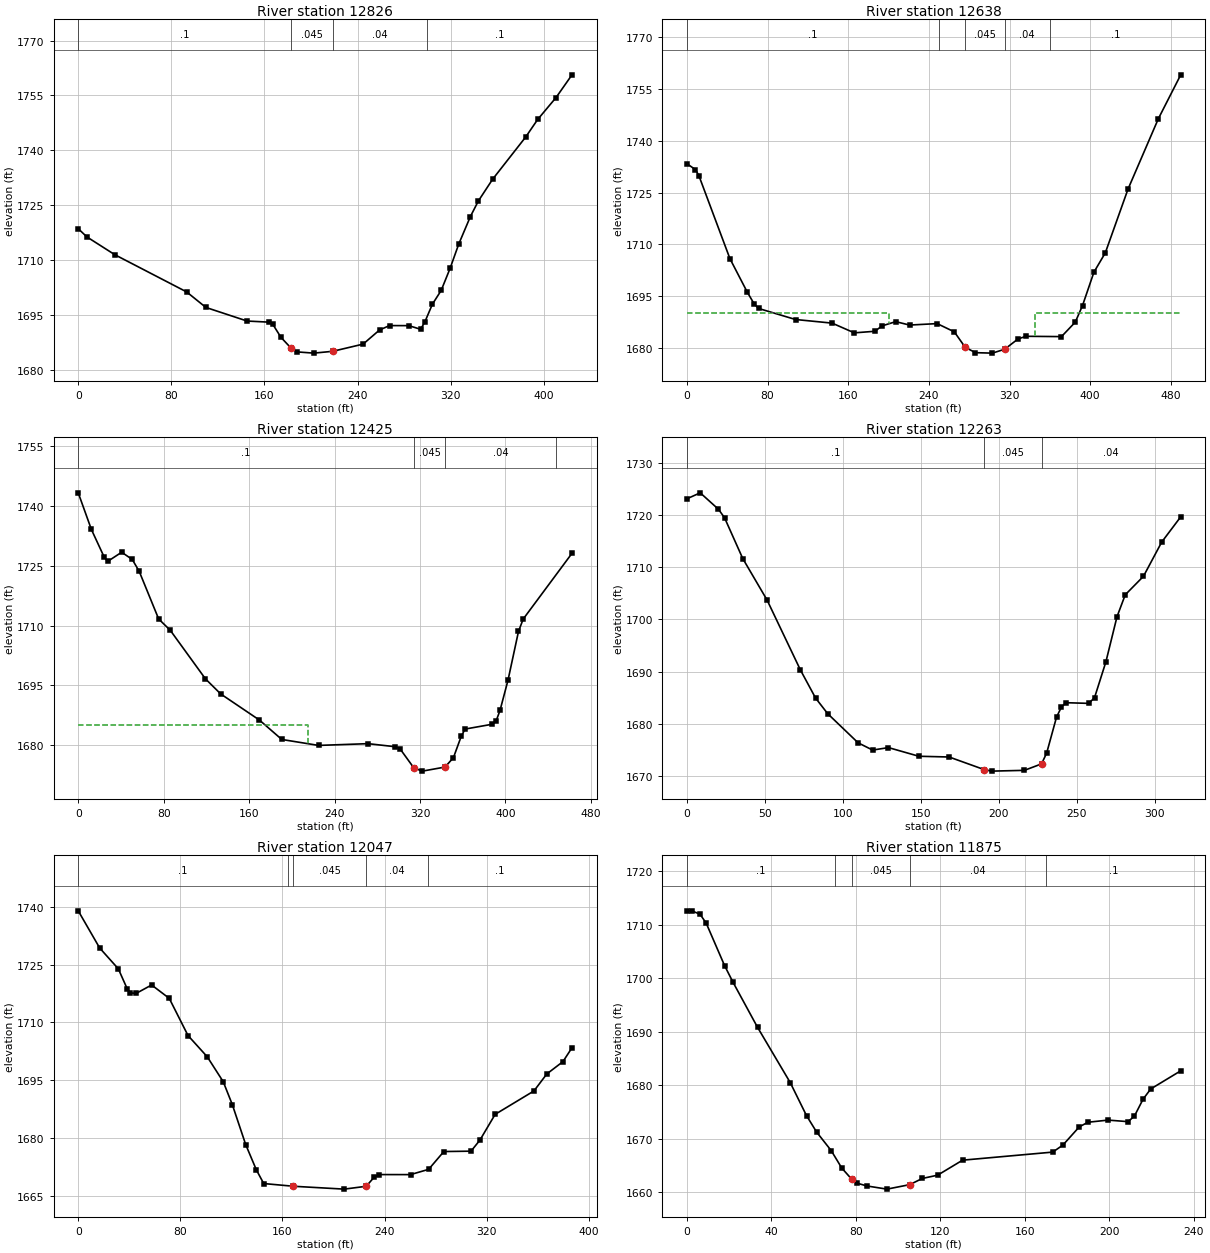
Type RM Length L Ch R = 1 ,12826   ,190.2,188.4,185.2
XS GIS Cut Line= 4
 2002217.7076199304959.1349731242002125.44519438305018.418297613
2002042.23114598305227.6771546272001966.83093448 305275.82364529
#Sta/Elev= 30
       0 1718.65     7.4 1716.41    31.4 1711.55    93.2 1701.38   109.7 1697.15
   145.1 1693.44   163.6 1693.14   167.1  1692.6   174.2 1688.99     183 1686.01
   188.3 1685.01   202.4 1684.68   218.61685.171   244.8 1687.14   258.9 1690.99
   267.5  1692.2   284.1 1692.18   294.2 1691.19   297.8 1693.15   304.3 1698.01
   311.9  1701.8   319.5 1707.78     327 1714.46     337 1721.97   343.9 1726.24
   356.1 1732.14   384.5 1743.66   394.8 1748.45   410.6 1754.44   424.3 1760.64
#Mann= 4 ,-1 , 0
       0      .1       0     183    .045       0   218.6     .04       0
  299.67      .1       0
Bank Sta=183,218.6
XS Rating Curve= 0 ,0
Exp/Cntr=0.3,0.1

Type RM Length L Ch R = 1 ,12638   ,209.7,213.2,216.7
XS GIS Cut Line= 3
2002002.32452254304752.1205130742001890.35267799305124.136258877
 2001840.9051562305212.599066965
#Sta/Elev= 30
       0 1733.34     8.4 1731.65    11.8 1729.91    42.6 1705.83    59.8 1696.12
    66.6 1692.72    71.1 1691.37   107.7 1688.17     144 1687.12     166  1684.3
   186.5 1684.76   193.4 1686.31   207.1 1687.55   220.8 1686.56   248.2 1686.98
   265.2 1684.59     276 1680.11   286.2 1678.55     303 1678.42   315.2 1679.56
   328.4 1682.53   336.3  1683.3   371.5 1683.21   385.2 1687.41   392.4 1692.23
   403.7  1701.9     415 1707.51   437.5 1725.98   467.6  1746.4   489.8 1759.13
#Mann= 5 ,-1 , 0
       0      .1       0     250     .04       0     276    .045       0
   315.2     .04       0     360      .1       0
#XS Ineff= 2 , 0
             200    1690     345            1690
Permanent Ineff=
       F       F
Bank Sta=276,315.2
XS Rating Curve= 0 ,0
Exp/Cntr=0.3,0.1

Type RM Length L Ch R = 1 ,12425   ,159.3,161.8,165.2
XS GIS Cut Line= 3
2001833.27575224 304680.221997072001828.16311216304737.132000736
2001654.55912639305103.198410575
#Sta/Elev= 30
       0 1743.33    12.3 1734.15    24.2 1727.27    27.5 1726.12    40.7 1728.43
    50.6 1726.61    57.1 1723.63    75.3 1711.69    86.2 1708.84   119.1 1696.67
   133.4 1692.88   169.7 1686.32   190.6 1681.46     225 1679.97   271.4 1680.41
   296.8 1679.64   301.4 1679.08   314.31674.306   322.2 1673.52   343.4 1674.54
   351.3  1676.9   358.6 1682.26   362.2 1684.07   387.6 1685.28   391.2 1686.07
   394.9 1688.74   402.4 1696.34   412.2 1708.56   416.6 1711.66   462.3 1728.16
#Mann= 4 ,-1 , 0
       0      .1       0   314.3    .045       0   343.4     .04       0
  447.14      .1       0
#XS Ineff= 2 , 0
             215    1685
Permanent Ineff=
       F       F
Bank Sta=314.3,343.4
XS Rating Curve= 0 ,0
Exp/Cntr=0.3,0.1

Type RM Length L Ch R = 1 ,12263   ,202.6,216,229.2
XS GIS Cut Line= 2
 2001689.7361603304716.8578144392001518.92969259304983.662529458
#Sta/Elev= 30
       0 1723.13     8.5 1724.27    20.2 1721.12    24.1  1719.5    35.8 1711.67
    51.4 1703.71    72.8  1690.3    82.5 1684.93    90.3 1681.92   109.8 1676.34
   119.1 1674.95   129.3 1675.42   148.8 1673.76   168.2 1673.62   190.71671.203
   195.5 1670.91   216.5 1671.06   227.51672.298   230.8 1674.39   237.1 1681.25
   240.3 1683.23   243.2 1684.03   257.8  1683.9   261.5    1685   268.8 1691.88
   275.9  1700.5   281.2 1704.72   292.9 1708.27   304.6 1714.83   316.8 1719.67
#Mann= 3 ,-1 , 0
       0      .1       0   190.7    .045       0   227.5     .04       0
Bank Sta=190.7,227.5
XS Rating Curve= 0 ,0
Exp/Cntr=0.3,0.1

Type RM Length L Ch R = 1 ,12047   ,183.7,172.1,156.2
XS GIS Cut Line= 4
2001572.52183282304598.9310837852001510.95957536304682.728294375
2001318.78525343304810.4593900272001286.02392077304850.916305097
#Sta/Elev= 30
       0 1738.97    16.8 1729.32    31.4 1723.91    38.4 1718.69    40.8 1717.64
    45.5 1717.55    57.5 1719.71    71.3 1716.24      86 1706.58   101.1 1701.05
   113.6 1694.58   120.7 1688.65   131.2 1678.25   139.6 1671.65   145.3 1668.14
   168.61667.433   208.4 1666.69   225.61667.427   231.9 1669.82   235.9 1670.47
   260.3 1670.46   274.5 1671.83   286.4 1676.45   307.7 1676.55   314.7 1679.43
   326.6 1686.11     357 1692.19   367.1 1696.61   379.7  1699.8   386.8 1703.41
#Mann= 5 ,-1 , 0
       0      .1       0  163.98     .04       0   168.6    .045       0
   225.6     .04       0  273.98      .1       0
Bank Sta=168.6,225.6
XS Rating Curve= 0 ,0
Exp/Cntr=0.3,0.1

Type RM Length L Ch R = 1 ,11875   ,170.3,172.2,175.7
XS GIS Cut Line= 2
2001359.25125142304541.6379200532001234.43017881304739.271285011
#Sta/Elev= 30
       0  1712.6     2.3 1712.64     6.2    1712     9.1 1710.34    17.8 1702.41
    21.7 1699.37    33.4 1690.88    48.9 1680.54    56.6 1674.37    61.4 1671.29
    68.3 1667.83    73.3 1664.57    78.1 1662.44    80.5 1661.75    85.2 1661.22
    94.7 1660.63   105.5 1661.47   111.4 1662.62   118.7 1663.24   130.5 1666.04
   173.2 1667.55     178 1668.86   185.8 1672.28   189.9 1673.13   199.4 1673.53
   208.9 1673.24   211.9  1674.3     216 1677.46   219.6 1679.35   233.8 1682.74
#Mann= 5 ,-1 , 0
       0      .1       0      70     .04       0    78.1    .045       0
   105.5     .04       0     170      .1       0
Bank Sta=78.1,105.5
XS Rating Curve= 0 ,0
Exp/Cntr=0.3,0.1

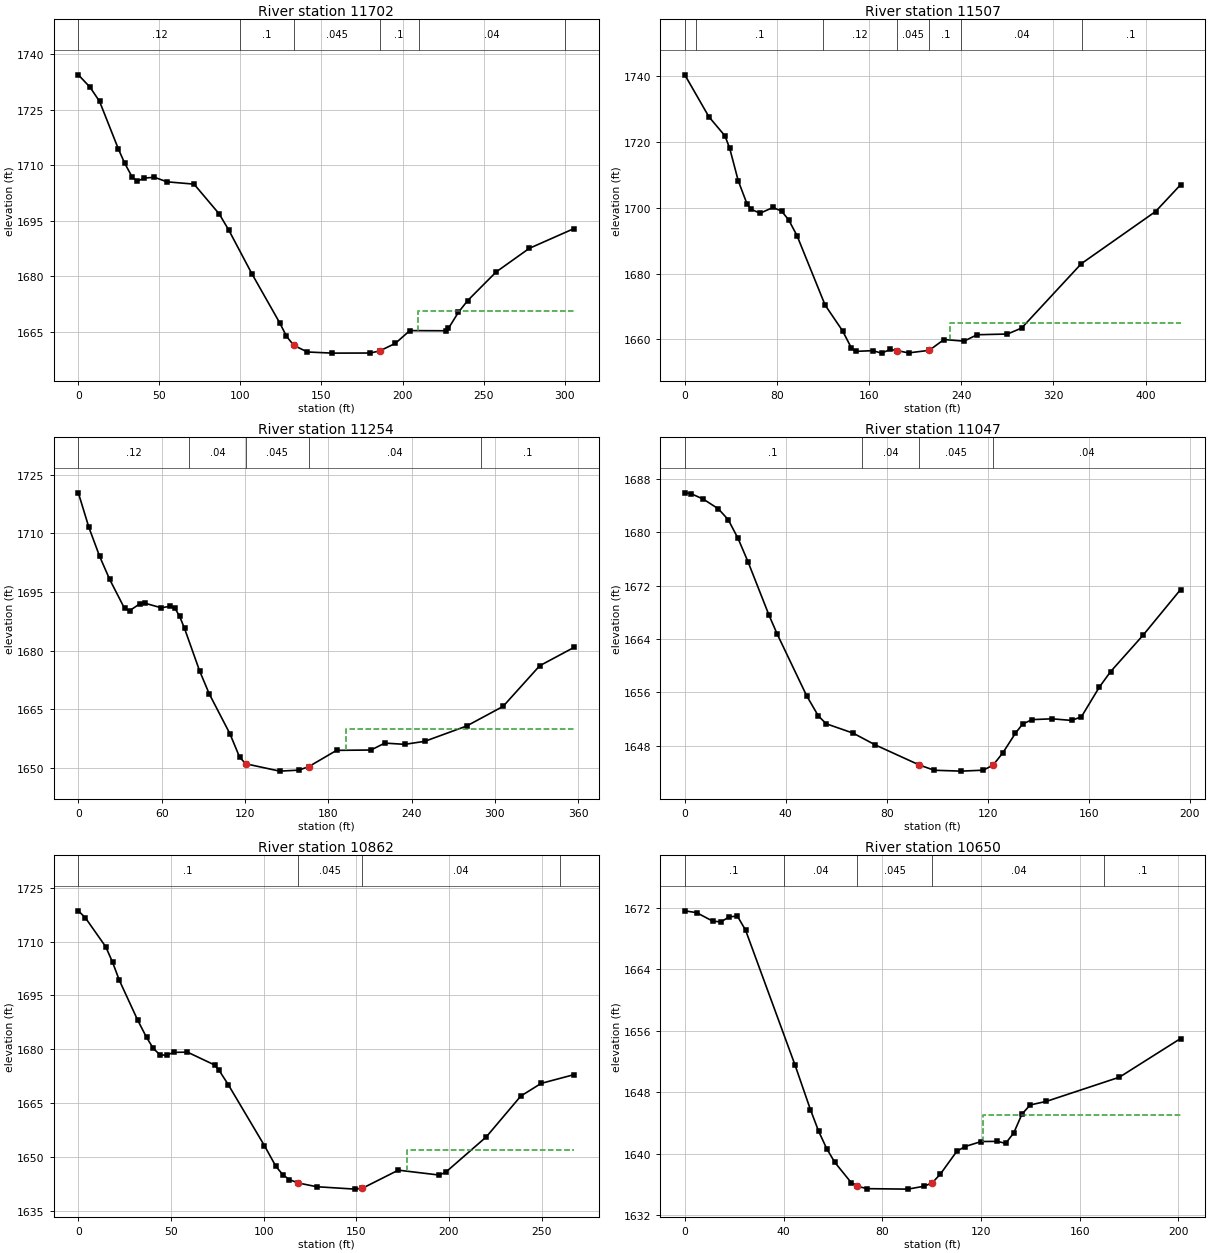
Type RM Length L Ch R = 1 ,11702   ,198.1,195.2,193.1
XS GIS Cut Line= 2
2001235.92524954304420.9797150522001072.22756532304679.360010509
#Sta/Elev= 30
       0  1734.4     7.2 1731.07    13.1 1727.22    24.7 1714.38    28.6 1710.53
    33.3 1706.74    36.4 1705.69    40.7 1706.51    46.9 1706.74    54.7 1705.51
    71.4 1704.88    86.9 1696.84    92.8 1692.49     107 1680.74   124.3 1667.38
   128.4 1663.82   132.91661.348   141.3 1659.56   156.8 1659.25   180.1 1659.28
   185.9 1659.84   195.6 1661.89   204.5 1665.33   226.7 1665.29   228.3 1665.91
   234.5 1670.28   240.2 1673.44   257.8 1681.18   278.2 1687.54   305.9  1692.9
#Mann= 6 ,-1 , 0
       0     .12       0     100      .1       0   132.9    .045       0
   185.9      .1       0     210     .04       0     300      .1       0
#XS Ineff= 2 , 0
                          209.85         1670.69
Permanent Ineff=
       F       F
Bank Sta=132.9,185.9
XS Rating Curve= 0 ,0
Exp/Cntr=0.3,0.1

Type RM Length L Ch R = 1 ,11507   ,254.9,253.5,250.7
XS GIS Cut Line= 3
2001073.48221921304296.5041987212000903.92714369304596.339612145
2000882.52087623304679.535200742
#Sta/Elev= 30
       0 1740.42    20.9 1727.67    34.8 1721.88    38.9 1718.17    46.4 1708.19
      54 1701.17    57.7 1699.53    65.3 1698.33    76.6 1700.09    84.1 1698.95
    90.2 1696.29    97.4 1691.52   121.8  1670.4   136.9  1662.6   144.4  1657.5
   148.2 1656.32   163.2 1656.54   170.8 1655.79   178.3  1656.9     1841656.578
   194.2 1655.86   212.2 1656.64     225 1659.93   242.4 1659.43   253.7 1661.38
   280.1  1661.6   292.4 1663.42   344.2 1682.99   408.6 1698.84   430.4    1707
#Mann= 7 ,-1 , 0
       0     .12       0      10      .1       0     120     .12       0
     184    .045       0   212.2      .1       0     240     .04       0
  344.46      .1       0
#XS Ineff= 2 , 0
                           230.4            1665
Permanent Ineff=
       F       F
Bank Sta=184,212.2
XS Rating Curve= 0 ,0
Exp/Cntr=0.3,0.1

Type RM Length L Ch R = 1 ,11254   ,203.8,206.5,209
XS GIS Cut Line= 2
2000809.99748078304234.4125438672000662.54437461304559.598237301
#Sta/Elev= 30
       0 1720.38     7.6 1711.54    15.3 1704.17    22.5 1698.29    33.3 1690.81
    36.9 1690.23    44.1 1691.96    47.7 1692.18    59.6 1690.99    65.7 1691.33
    69.6 1690.84    72.9 1688.83    76.5 1685.69    87.3 1674.88    94.3 1668.95
   109.2 1658.75   116.1 1652.82   120.51651.091     145 1649.21   158.8 1649.46
     166 1650.37     186 1654.52   210.8 1654.61   220.7 1656.38     235 1656.06
   249.4 1656.82   279.6 1660.74   305.9 1665.76   332.3 1676.16   357.1 1680.87
#Mann= 5 ,-1 , 0
       0     .12       0      80     .04       0   120.5    .045       0
     166     .04       0     290      .1       0
#XS Ineff= 2 , 0
                             193            1660
Permanent Ineff=
       F       F
Bank Sta=120.5,166
XS Rating Curve= 0 ,0
Exp/Cntr=0.3,0.1

Type RM Length L Ch R = 1 ,11047   ,188.6,185,182.9
XS GIS Cut Line= 2
2000615.83162782304207.5579904342000510.59033131304373.374219238
#Sta/Elev= 30
       0 1685.92     2.5 1685.79     7.3 1684.98    13.3 1683.52    17.2 1681.89
    21.1 1679.08      25 1675.62    33.4 1667.54    36.6 1664.75    48.3 1655.48
    52.9 1652.48      56 1651.31    66.7  1649.9    75.5 1648.13    92.9 1645.13
    98.8 1644.34   109.5 1644.21   118.2 1644.35   122.1  1645.1     126 1646.96
   130.9 1649.85   133.8 1651.27   137.6 1651.93   145.4 1652.05   153.2 1651.81
   157.1 1652.35   164.2  1656.8   168.7 1659.14   181.5 1664.57   196.4 1671.43
#Mann= 4 ,-1 , 0
       0      .1       0      70     .04       0    92.9    .045       0
   122.1     .04       0
Bank Sta=92.9,122.1
XS Rating Curve= 0 ,0
Exp/Cntr=0.3,0.1

Type RM Length L Ch R = 1 ,10862   ,223.1,212.1,203
XS GIS Cut Line= 2
2000466.30546424304074.3385209322000346.11415242304313.379630626
#Sta/Elev= 30
       0 1718.55     3.8 1716.61    14.8 1708.54    18.5 1704.21    22.1 1699.25
      32 1688.16    36.8 1683.34    40.5 1680.24    44.2 1678.41    47.8 1678.42
    51.5 1679.16    58.9 1679.22    73.5 1675.66      76 1674.13    80.9 1670.19
   100.4 1653.24   106.6 1647.45   110.5 1645.03   113.9 1643.77   118.31642.857
   128.6 1641.77   149.3  1641.1   153.31641.345   172.7 1646.38   194.7 1645.02
   198.2 1645.77   220.2 1655.65   238.8    1667   249.8 1670.53   267.6 1672.97
#Mann= 4 ,-1 , 0
       0      .1       0   118.3    .045       0   153.3     .04       0
     260      .1       0
#XS Ineff= 2 , 0
                           177.6            1652
Permanent Ineff=
       F       F
Bank Sta=118.3,153.3
XS Rating Curve= 0 ,0
Exp/Cntr=0.3,0.1

Type RM Length L Ch R = 1 ,10650   ,186,178.3,171.8
XS GIS Cut Line= 2
2000204.65632982304072.9470297812000186.30028973304273.027866751
#Sta/Elev= 30
       0 1671.64     4.8  1671.4    11.4 1670.28    14.7 1670.21      18 1670.86
    21.3 1670.95    24.6 1669.14    44.6 1651.61    50.9 1645.75    54.2 1642.95
    57.5 1640.66    60.8 1638.87    67.4 1636.25    69.9 1635.75      74 1635.45
    90.4 1635.39      97 1635.77   100.3 1636.22   103.6 1637.37   110.2 1640.31
   113.5 1640.93   120.1 1641.59   126.7 1641.61     130 1641.35   133.3 1642.72
   136.6 1645.15   139.9 1646.35   146.5 1646.82   176.1 1649.97   200.9 1655.01
#Mann= 5 ,-1 , 0
       0      .1       0      40     .04       0    69.9    .045       0
   100.3     .04       0     170      .1       0
#XS Ineff= 2 , 0
                             121            1645
Permanent Ineff=
       F       F
Bank Sta=69.9,100.3
XS Rating Curve= 0 ,0
Exp/Cntr=0.3,0.1