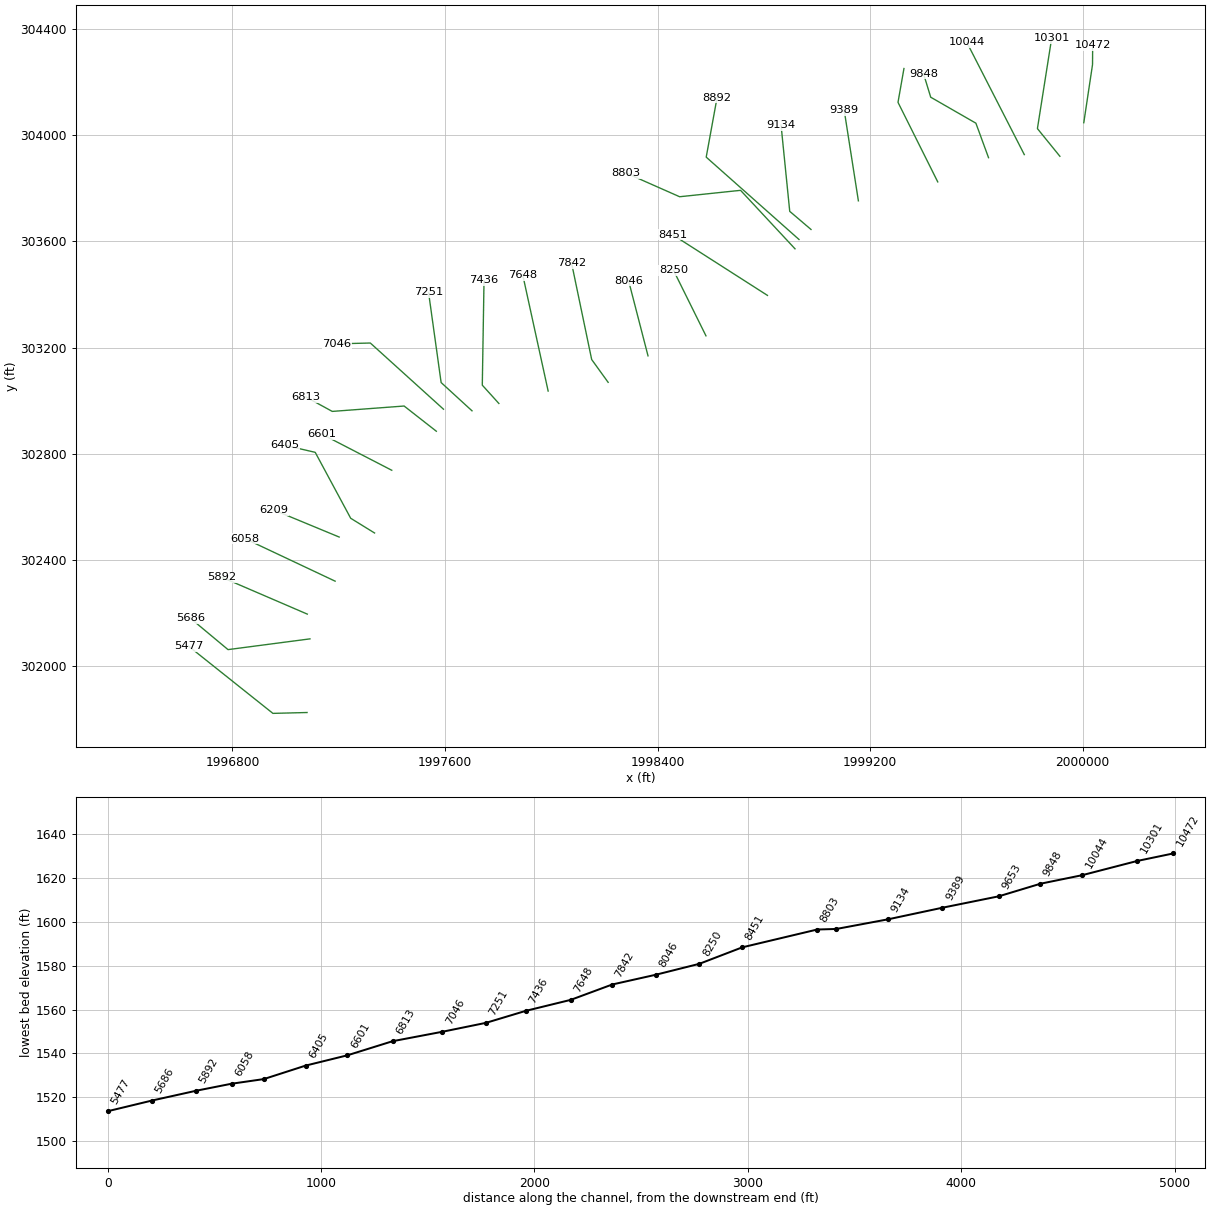
HEC-RAS study MEADOWCK_A.prj: MEADOWCK_A

--- MEADOWCK_A.g01 (geometry) --- (continued)

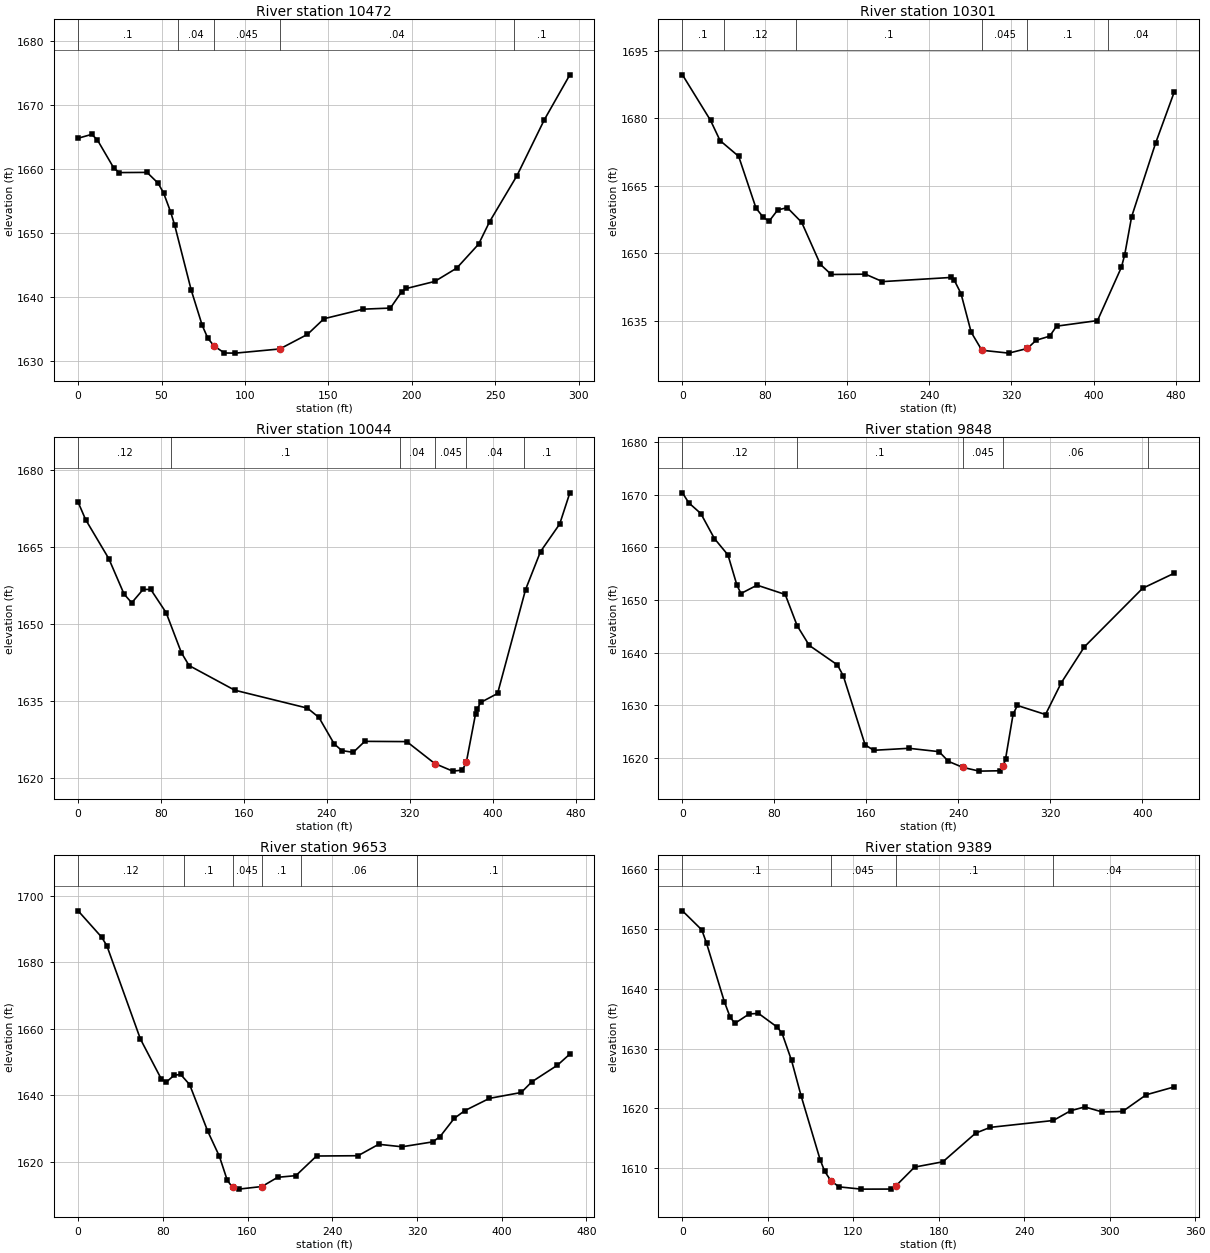
Type RM Length L Ch R = 1 ,10472   ,171,170.4,171.5
XS GIS Cut Line= 3
2000004.12881203304046.7480994812000037.00449701304265.685450716
 2000037.5477118304339.101518932
#Sta/Elev= 30
       0 1664.78     8.1 1665.38    11.4 1664.58    21.4 1660.13    24.7 1659.43
    41.3 1659.46    47.9 1657.79    51.2 1656.28    55.5 1653.27    57.9 1651.22
    67.8 1641.12    74.4 1635.62    77.8  1633.6    81.5 1632.42    87.7 1631.32
    94.3  1631.3   120.9 1631.95   137.5 1634.22   147.4 1636.66   170.9 1638.15
   187.2 1638.32   193.9 1640.83   196.8 1641.37   213.8 1642.47     227 1644.55
   240.1 1648.28   246.7 1651.78   263.1 1658.95   279.5 1667.66   294.8 1674.66
#Mann= 5 ,-1 , 0
       0      .1       0      60     .04       0    81.5    .045       0
   120.9     .04       0  261.39      .1       0
Bank Sta=81.5,120.9
XS Rating Curve= 0 ,0
Exp/Cntr=0.3,0.1

Type RM Length L Ch R = 1 ,10301   ,242.1,256.9,272.4
XS GIS Cut Line= 3
1999914.10753901303920.378155034  1999829.586267304024.621063395
1999883.15351361304364.577696347
#Sta/Elev= 30
       0 1689.67    27.3 1679.56    36.6 1675.06    54.7 1671.56    71.6 1660.04
    78.6 1658.03    84.3 1657.14    92.7 1659.66     102 1660.16     116  1656.9
   134.2 1647.56   144.8 1645.31     178 1645.38   194.6 1643.73   261.1 1644.65
   264.3 1644.11     271 1641.08   280.9 1632.49   291.31628.481   317.5 1627.84
   335.6 1628.88   344.1  1630.7   357.3 1631.61     364 1633.83   403.8 1635.07
   427.1 1646.93   430.3 1649.72     437 1658.13   460.3 1674.47   478.4 1685.81
#Mann= 6 ,-1 , 0
       0      .1       0      40     .12       0     110      .1       0
   291.3    .045       0   335.6      .1       0   414.2     .04       0
Bank Sta=291.3,335.6
XS Rating Curve= 0 ,0
Exp/Cntr(USF)=0,0
Exp/Cntr=0.3,0.1

Type RM Length L Ch R = 1 ,10044   ,181.9,196.1,211.2
XS GIS Cut Line= 2
1999780.18067809303926.7158163121999564.08812343304348.982986725
#Sta/Elev= 30
       0 1673.75     7.2 1670.37    29.6 1662.75    44.3 1655.86    51.7 1654.16
    62.7 1656.77    70.1 1656.75    84.9 1652.23    99.6 1644.44     107 1641.94
     151 1637.14   221.2 1633.64   232.3 1631.82     247 1626.67   254.4 1625.37
   265.4 1625.03   276.5 1627.17     317 1627.12     3441622.848   361.3 1621.37
   370.5 1621.56   374.41623.052   383.4 1632.58   385.1 1633.56   388.4 1634.76
   404.6  1636.5   431.6 1656.74     446 1664.13   464.5  1669.5   474.3 1675.58
#Mann= 6 ,-1 , 0
       0     .12       0      90      .1       0     310     .04       0
     344    .045       0   374.4     .04       0     430      .1       0
Bank Sta=344,374.4
XS Rating Curve= 0 ,0
Exp/Cntr=0.3,0.1

Type RM Length L Ch R = 1 ,9848    ,206,195.1,176.5
XS GIS Cut Line= 4
   1999645.59769303915.0599940461999598.06979103304044.947984888
1999427.99213804304142.8410624381999400.70730884304231.921901809
#Sta/Elev= 30
       0 1670.36     5.5 1668.46      16 1666.42    27.8 1661.67    39.6 1658.55
    47.4  1652.8    50.9 1651.22    64.9 1652.81    89.4 1651.04    99.8 1645.09
   110.3 1641.36   134.8 1637.65   139.9 1635.57   158.9 1622.45   166.4 1621.42
     197  1621.8   223.2 1621.16   231.4 1619.31   243.91618.171   258.2 1617.46
   276.2 1617.53     279 1618.34   281.1 1619.86   287.6 1628.27   291.3 1629.94
   315.8 1628.22   329.5 1634.25   349.6 1641.08   400.3 1652.22   427.7 1655.07
#Mann= 5 ,-1 , 0
       0     .12       0     100      .1       0   243.9    .045       0
     279     .06       0  404.55      .1       0
Bank Sta=243.9,279
XS Rating Curve= 0 ,0
Exp/Cntr=0.3,0.1

Type RM Length L Ch R = 1 ,9653    ,273.1,263.8,254.7
XS GIS Cut Line= 3
1999454.47948336303823.8232189821999304.87084194304123.424456671
1999327.24891044304250.876077608
#Sta/Elev= 30
       0 1695.52    22.1 1687.63    27.1 1685.04    58.8 1656.92    78.4 1644.96
    83.3 1643.95    90.6    1646    96.8 1646.26   105.3 1643.19   122.4 1629.14
   133.4 1621.59   140.8  1614.4   145.81612.231   151.7 1611.72   173.61612.507
   188.4 1615.28   205.6 1615.78   225.1 1621.69   264.3 1621.78   283.8 1625.22
   305.8 1624.47   334.9 1625.95   341.8 1627.56   355.1 1633.02   365.1 1635.35
   388.4 1639.05   418.4 1640.82   428.4 1644.03   452.6 1649.04   464.3 1652.39
#Mann= 6 ,-1 , 0
       0     .12       0     100      .1       0   145.8    .045       0
   173.6      .1       0     210     .06       0     320      .1       0
Bank Sta=145.8,173.6
XS Rating Curve= 0 ,0
Exp/Cntr=0.3,0.1

Type RM Length L Ch R = 1 ,9389    ,258.2,255.3,253.7
XS GIS Cut Line= 2
1999155.74199262 303752.629116611999102.35657591304093.774949938
#Sta/Elev= 30
       0 1653.03    13.6 1649.84    16.9 1647.64    29.4 1637.86    33.5 1635.26
    36.8 1634.22    46.8 1635.79    53.4 1635.89    66.7 1633.57      70 1632.53
    76.6 1628.04    83.3 1622.13    96.7 1611.43    99.9 1609.49   104.2 1607.94
   109.9  1606.9   125.5 1606.52   146.4 1606.53   149.7 1607.02     163  1610.2
   182.9 1611.09   205.9 1615.88   216.1 1616.84   260.4 1617.99   272.6 1619.62
   282.5 1620.26   294.9 1619.41   309.1  1619.5   325.7 1622.29   345.3  1623.6
#Mann= 4 ,-1 , 0
       0      .1       0   104.2    .045       0   149.7      .1       0
     260     .04       0
Bank Sta=104.2,149.7
XS Rating Curve= 0 ,0
Exp/Cntr(USF)=0,0
Exp/Cntr=0.3,0.1

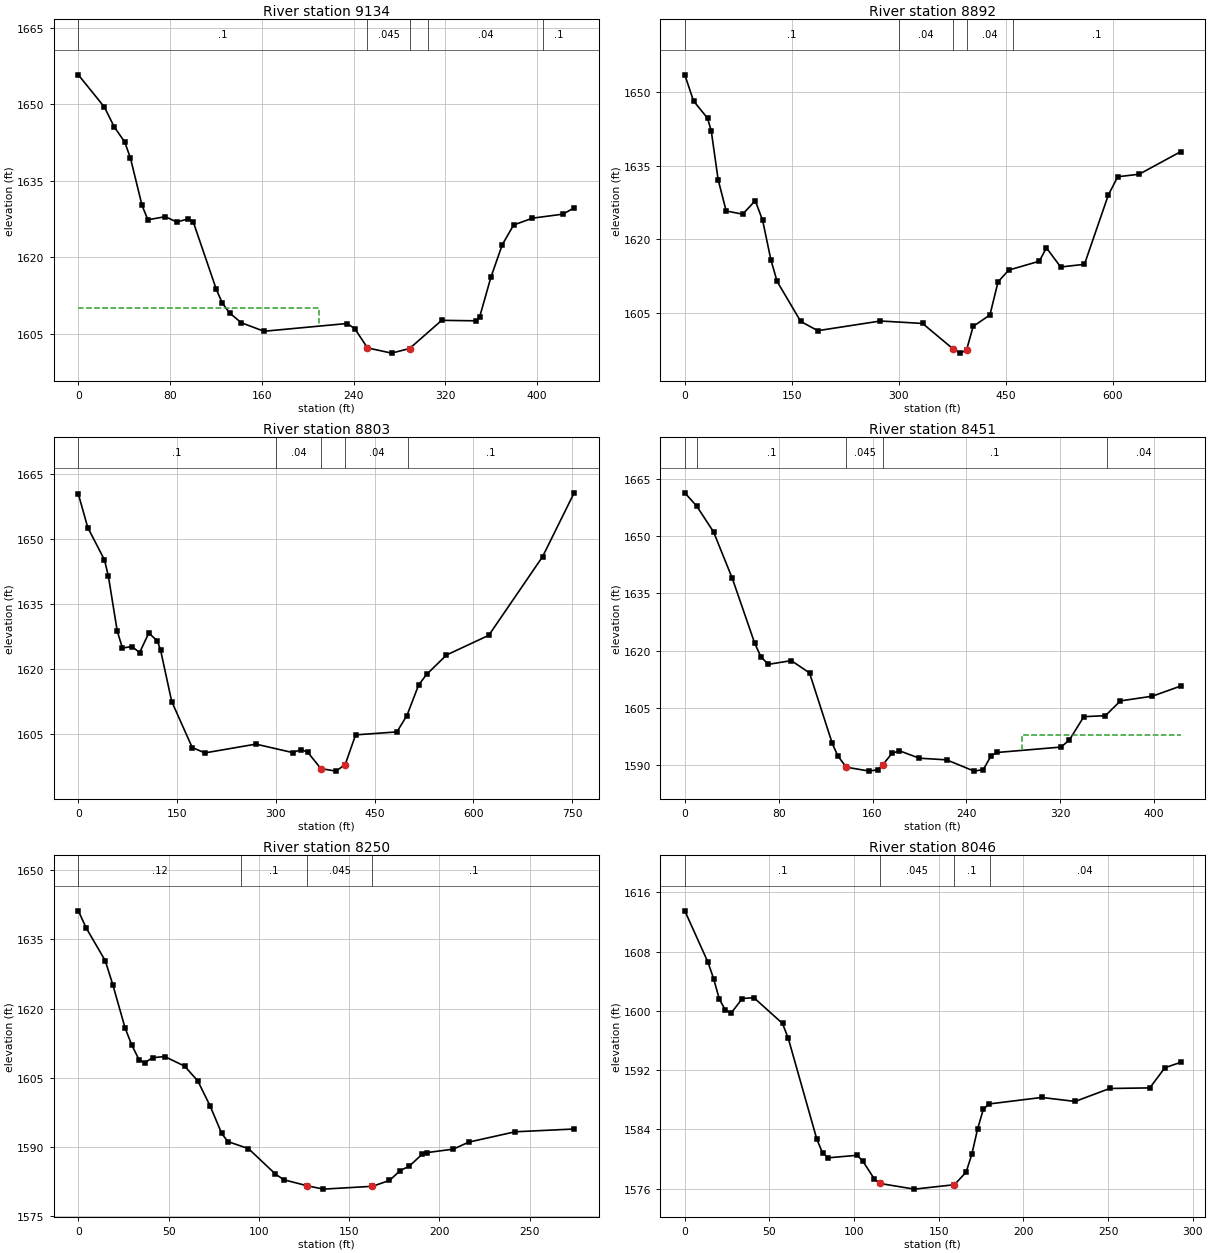
Type RM Length L Ch R = 1 ,9134    ,227,241.9,254.4
XS GIS Cut Line= 3
1998977.46981518303644.7306525431998897.37530803303712.925114329
 1998864.6437515304038.383247345
#Sta/Elev= 30
       0 1655.81    22.7 1649.49    31.3  1645.6    40.4 1642.65    45.4 1639.51
    55.5 1630.23    60.6 1627.38    75.8 1627.98    85.9 1626.94      96 1627.56
   100.3 1626.89   120.3 1613.73   125.6 1610.99   132.1 1609.06   142.1 1607.18
   161.9 1605.51   234.4 1607.03     241 1606.03   252.1 1602.25   273.1 1601.22
   288.81602.121   316.8 1607.65   346.5 1607.56   349.8 1608.24   359.7  1616.1
   369.6 1622.47   379.5 1626.35   395.9 1627.69   422.4 1628.48   432.3  1629.7
#Mann= 5 ,-1 , 0
       0      .1       0   252.1    .045       0   288.8      .1       0
  305.19     .04       0  405.19      .1       0
#XS Ineff= 2 , 0
           209.9    1610
Permanent Ineff=
       F       F
Bank Sta=252.1,288.8
XS Rating Curve= 0 ,0
Exp/Cntr=0.3,0.1

Type RM Length L Ch R = 1 ,8892    ,69.6,89.6,107
XS GIS Cut Line= 3
1998932.24917568303607.0483982111998583.01900096 303917.13842359
1998623.90210389304141.399310323
#Sta/Elev= 30
       0 1653.47    12.2 1648.17    31.9 1644.63    37.1 1642.05    46.7 1632.15
      58 1625.76    81.2  1625.1    98.7 1627.86   109.1 1623.85   120.7 1615.79
   129.4 1611.41   162.5 1603.27   186.4 1601.39   274.2 1603.36   333.3 1602.86
     376 1597.68   385.7 1596.82   394.9 1597.44   404.2 1602.27   427.7 1604.59
   439.1 1611.33     454 1613.72   496.9 1615.53   506.9 1618.25   526.9 1614.35
   560.2  1614.9   593.7 1629.02   606.9 1632.72   636.9 1633.24     695 1637.82
#Mann= 5 ,-1 , 0
       0      .1       0     300     .04       0     376    .045       0
   394.9     .04       0     460      .1       0
Bank Sta=376,394.9
XS Rating Curve= 0 ,0
Exp/Cntr(USF)=0,0
Exp/Cntr=0.3,0.1

Type RM Length L Ch R = 1 ,8803    ,362.2,351.5,328.4
XS GIS Cut Line= 4
1998917.24120875303571.8368068921998712.31027059 303792.09961642
1998482.99424416303767.9786985391998280.39718557  303857.5830122
#Sta/Elev= 30
       0 1660.31    14.3 1652.59    39.7 1645.15    45.7 1641.35    59.1 1628.75
      67 1624.88    81.4 1625.22    93.1 1623.84     107 1628.33     120 1626.51
   124.8 1624.48   141.8 1612.58     173 1601.99   192.2 1600.76   269.7 1602.78
   325.4 1600.84   338.6 1601.52   348.5 1600.89   368.3 1597.15   391.4 1596.57
   405.31598.094   421.1 1604.91   483.8 1605.59     499 1609.35   516.9 1616.41
   528.9 1618.81   559.1 1623.27   623.4 1627.81   705.1  1645.9     753 1660.57
#Mann= 5 ,-1 , 0
       0      .1       0     300     .04       0   368.3    .045       0
   405.3     .04       0  500.85      .1       0
Bank Sta=368.3,405.3
XS Rating Curve= 0 ,0
Exp/Cntr(USF)=0,0
Exp/Cntr=0.3,0.1

Type RM Length L Ch R = 1 ,8451    ,211.9,201,183.8
XS GIS Cut Line= 2
1998813.51709068303396.4063629531998457.63356947303624.293463523
#Sta/Elev= 30
       0  1661.3    10.1 1657.85    24.5 1651.07    40.5 1638.89    59.6  1621.9
    64.9 1618.34    71.2 1616.39    90.8 1617.36   106.3 1614.15   125.7 1595.67
   130.5 1592.37   137.7 1589.46     157 1588.45   164.8  1588.8   168.71590.086
   176.5 1593.05   182.8 1593.77   199.8 1591.82   223.2 1591.38   246.6 1588.43
   254.4 1588.84   261.2  1592.5   266.1 1593.31   320.6 1594.73   327.7 1596.55
   340.1 1602.69   358.5 1602.95   371.3 1606.82   398.5 1608.05   422.6  1610.7
#Mann= 5 ,-1 , 0
       0     .12       0      10      .1       0   137.7    .045       0
   168.7      .1       0     360     .04       0
#XS Ineff= 2 , 0
                             287            1598
Permanent Ineff=
       F       F
Bank Sta=137.7,168.7
XS Rating Curve= 0 ,0
Exp/Cntr=0.3,0.1

Type RM Length L Ch R = 1 ,8250    ,209.4,203.9,196.9
XS GIS Cut Line= 2
1998582.05070016303244.1782219331998460.20124003303490.265939528
#Sta/Elev= 30
       0 1641.14     4.4  1637.4    14.9 1630.35    19.1 1625.14    25.9 1615.77
    29.5 1612.18    33.8 1608.77    36.8  1608.3    41.2 1609.35    47.8 1609.61
    58.8 1607.54    66.1 1604.37      73  1598.9    79.4 1592.96    82.8  1591.2
    94.2 1589.68     109 1584.23   113.7 1582.95   126.81581.631   135.7 1580.91
   162.91581.523   172.3 1582.79   178.3 1584.92   183.3 1585.89   190.5 1588.49
     193 1588.81   207.7 1589.57   216.2 1591.08   241.9 1593.32   274.6 1593.92
#Mann= 4 ,-1 , 0
       0     .12       0      90      .1       0   126.8    .045       0
   162.9      .1       0
Bank Sta=126.8,162.9
XS Rating Curve= 0 ,0
Exp/Cntr=0.3,0.1

Type RM Length L Ch R = 1 ,8046    ,209.5,204.5,204.1
XS GIS Cut Line= 2
1998363.94576291303168.8248754741998290.68890533303452.327618086
#Sta/Elev= 30
       0 1613.51    13.7 1606.56      17 1604.36    20.4 1601.58    23.8 1600.18
    27.2 1599.66      34 1601.67    40.8 1601.78    57.7  1598.3    61.1 1596.29
      78 1582.64    81.4  1580.8    84.8 1580.16   101.8  1580.5   105.1 1579.72
   111.9 1577.31   115.11576.698   135.6 1575.93   159.21576.527   166.1 1578.21
   169.5 1580.63   172.9 1584.06   176.3 1586.72   179.7 1587.43   210.8 1588.31
   230.5 1587.77   250.9 1589.52   274.6  1589.6   283.5 1592.32   292.8 1593.05
#Mann= 4 ,-1 , 0
       0      .1       0   115.1    .045       0   159.2      .1       0
     180     .04       0
Bank Sta=115.1,159.2
XS Rating Curve= 0 ,0
Exp/Cntr=0.3,0.1

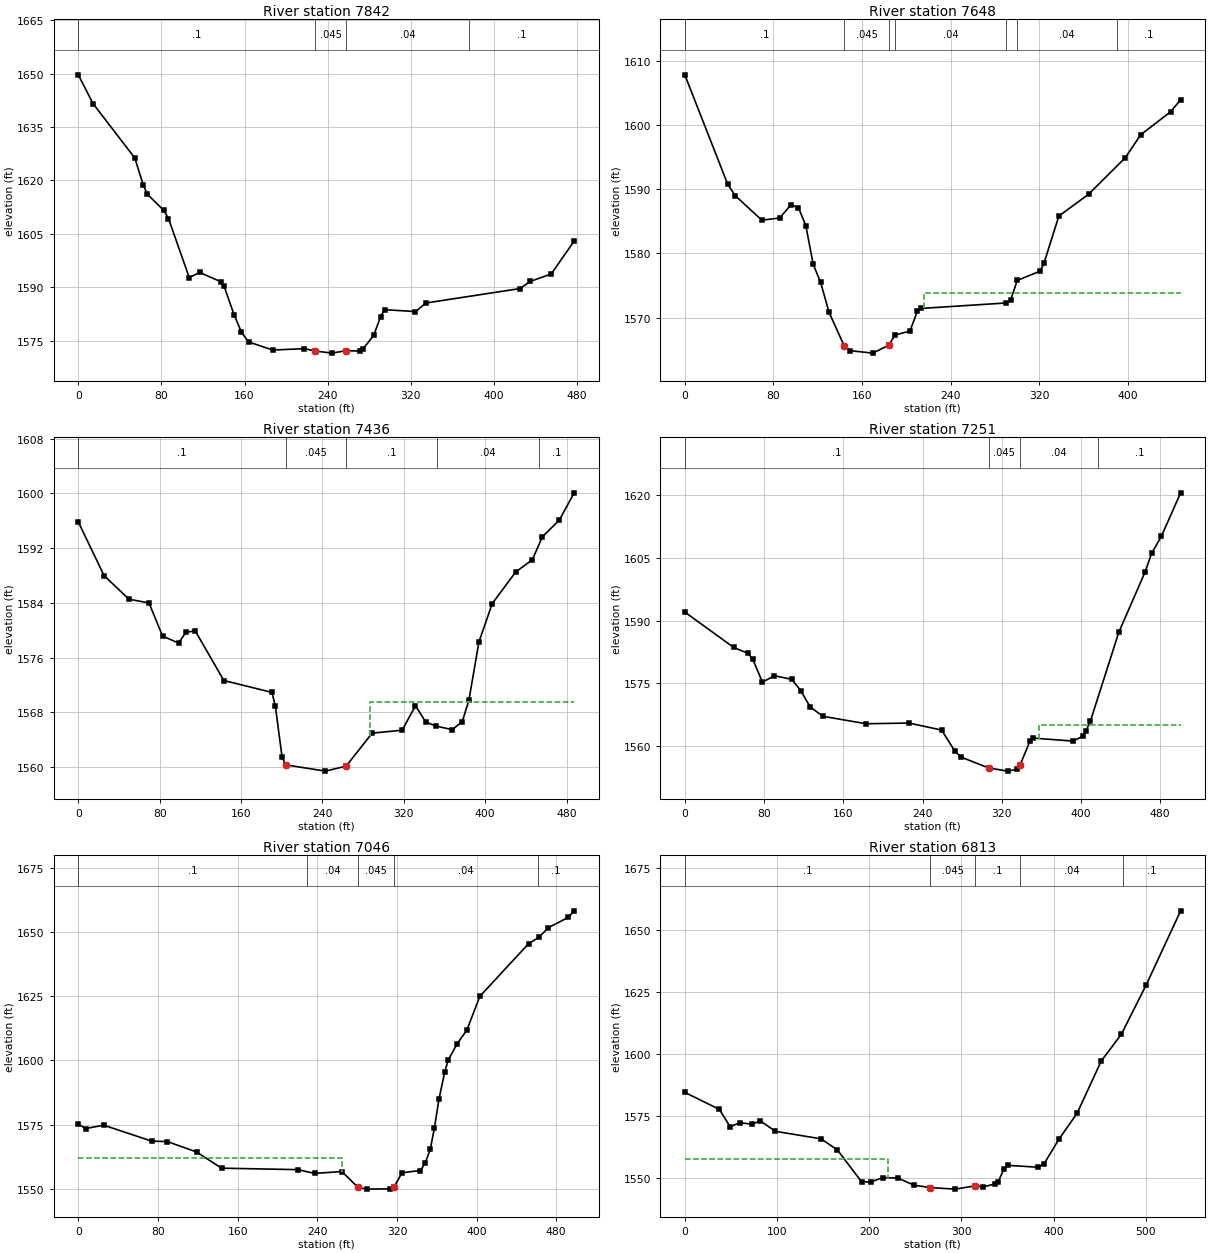
Type RM Length L Ch R = 1 ,7842    ,197.6,194,195.2
XS GIS Cut Line= 3
1998213.86051252303069.0264475911998151.94856875303154.824246799
 1998076.1414726303518.634098838
#Sta/Elev= 30
       0  1649.7    14.1 1641.63    54.4 1626.31    62.5 1618.72    66.5 1616.13
    82.2 1611.61    86.8 1609.31   106.8  1592.7   116.9 1594.15     137 1591.56
   140.3 1590.29     150 1582.24   157.1 1577.34   163.9 1574.62   187.2 1572.33
   217.4 1572.73   227.61572.093   244.2 1571.47   257.91572.163     271 1572.05
   274.4 1572.76   284.4 1576.46   291.1 1581.75   294.8 1583.69   324.6 1583.15
   334.7 1585.56   425.2 1589.62   435.2 1591.64   455.3 1593.71   477.4 1602.97
#Mann= 4 ,-1 , 0
       0      .1       0   227.6    .045       0   257.9     .04       0
   375.8      .1       0
Bank Sta=227.6,257.9
XS Rating Curve= 0 ,0
Exp/Cntr=0.3,0.1

Type RM Length L Ch R = 1 ,7648    ,219.3,211.5,205.5
XS GIS Cut Line= 2
1997988.12043266303036.0215648121997892.58107171303473.083925284
#Sta/Elev= 30
       0  1607.8    38.6 1590.82    45.4    1589    69.5 1585.17    85.7 1585.51
    95.7 1587.56   102.5 1587.14   109.2 1584.33   115.9 1578.27   122.6 1575.47
   130.1 1570.84   143.9 1565.58   149.4 1564.85   169.6 1564.47   183.9 1565.68
   189.8 1567.29   203.2 1567.91   209.9 1571.02   213.3 1571.43     290 1572.28
   293.9 1572.69     300 1575.79   320.7 1577.24   324.1 1578.47   337.5  1585.8
   364.4 1589.22   397.5  1594.9   411.4 1598.47   438.3 1602.04   447.4 1603.91
#Mann= 7 ,-1 , 0
       0      .1       0   143.9    .045       0   183.9      .1       0
     190     .04       0     290      .1       0     300     .04       0
     390      .1       0
#XS Ineff= 2 , 0
                          215.62         1573.84
Permanent Ineff=
       F       F
Bank Sta=143.9,183.9
XS Rating Curve= 0 ,0
Exp/Cntr=0.3,0.1

Type RM Length L Ch R = 1 ,7436    ,182.4,185.4,185.4
XS GIS Cut Line= 3
1997802.59877036302989.3937386111997740.26427733303058.319141278
1997746.76498891303452.787222194
#Sta/Elev= 30
       0 1595.83    25.3    1588    49.7 1584.55    69.5    1584    82.8 1579.17
    98.5 1578.14   105.9 1579.74     115  1579.9   143.1 1572.67   190.4 1570.93
   193.7 1568.94   200.3  1561.5   203.81560.348   242.9 1559.43   263.31560.157
   288.9 1564.98   318.4 1565.41   331.5 1568.99   341.4 1566.63   351.2 1566.03
   367.6 1565.49   377.5 1566.67     384 1569.78   393.9 1578.33     407 1583.92
     430 1588.52   446.4 1590.31   456.2 1593.66   472.9  1596.1   487.5 1600.09
#Mann= 5 ,-1 , 0
       0      .1       0   203.8    .045       0   263.3      .1       0
  352.93     .04       0  452.93      .1       0
#XS Ineff= 2 , 0
                           286.5          1569.5
Permanent Ineff=
       F       F
Bank Sta=203.8,263.3
XS Rating Curve= 0 ,0
Exp/Cntr=0.3,0.1

Type RM Length L Ch R = 1 ,7251    ,185.7,204.7,223.8
XS GIS Cut Line= 3
1997701.45613592302961.7497258171997585.30191197303068.154632207
1997537.98017481303407.911484387
#Sta/Elev= 30
       0 1592.07    49.3 1583.61    63.8 1582.19    68.5 1580.84    78.4  1575.3
    90.5 1576.83   107.9 1575.97   117.2 1573.24   126.5 1569.37   139.4 1567.12
   183.1 1565.33   226.3  1565.5   259.3 1563.82   272.5 1558.84   279.1 1557.33
   306.7 1554.76     326 1553.99   335.5 1554.42   338.71555.555   348.7 1561.32
     352 1561.89   391.8 1561.19   401.7 1562.31     405 1563.61   409.5 1565.95
   438.1 1587.18   464.6  1601.6   471.3 1606.14   481.2 1610.23   500.6 1620.62
#Mann= 4 ,-1 , 0
       0      .1       0   306.7    .045       0   338.7     .04       0
  417.52      .1       0
#XS Ineff= 2 , 0
                           357.6            1565
Permanent Ineff=
       F       F
Bank Sta=306.7,338.7
XS Rating Curve= 0 ,0
Exp/Cntr=0.3,0.1

Type RM Length L Ch R = 1 ,7046    ,207.4,233.3,256.4
XS GIS Cut Line= 3
1997594.17776489302967.7806441471997318.84663596303217.037209607
 1997192.3232652303213.903274565
#Sta/Elev= 30
       0 1575.26     7.3 1573.46    25.4  1574.8    73.6  1568.6    89.5  1568.4
   118.8 1564.35   143.9 1558.06   220.5 1557.49   237.4 1556.02   264.7 1556.76
   280.81550.624   289.9 1549.91   313.5 1550.02   317.31550.844   325.1 1556.29
   343.6 1557.15   348.3 1559.95   353.5 1565.41   357.6 1573.64   362.2  1584.9
   368.1 1595.62   371.4 1600.06   380.3 1606.36   390.2 1611.78   403.3 1624.95
   452.3 1645.42   462.4 1647.83   472.2 1651.65   491.9  1655.6     498 1658.19
#Mann= 5 ,-1 , 0
       0      .1       0     230     .04       0   280.8    .045       0
   317.3     .04       0   461.4      .1       0
#XS Ineff= 2 , 0
           265.3    1562
Permanent Ineff=
       F       F
Bank Sta=280.8,317.3
XS Rating Curve= 0 ,0
Exp/Cntr=0.3,0.1

Type RM Length L Ch R = 1 ,6813    ,227.8,211.6,202
XS GIS Cut Line= 4
1997567.24308594302884.811020011 1997446.0497067302979.736905887
1997175.55993653302959.4715805611997076.93712704303013.427170559
#Sta/Elev= 30
       0 1584.56    37.5 1577.72    49.1 1570.76    60.1 1572.36    72.5 1571.73
    81.9  1573.1    98.2 1568.88   147.7 1565.86   165.4  1561.4   191.7 1548.55
   201.6 1548.48   214.8 1550.25   231.2 1550.06   248.3 1547.19   265.9 1546.23
   293.2  1545.6     3151546.929   323.3 1546.48   336.5 1547.69   339.8 1548.56
   346.2 1553.83   350.1 1555.18   382.6 1554.43   389.2 1555.58   405.6 1565.67
   425.4 1576.18   451.4 1597.11   473.3 1607.95   500.2 1627.77   537.6 1657.67
#Mann= 5 ,-1 , 0
       0      .1       0   265.9    .045       0     315      .1       0
  363.94     .04       0  475.19      .1       0
#XS Ineff= 2 , 0
          220.67 1557.78
Permanent Ineff=
       F       F
Bank Sta=265.9,315
XS Rating Curve= 0 ,0
Exp/Cntr(USF)=0,0
Exp/Cntr=0.3,0.1

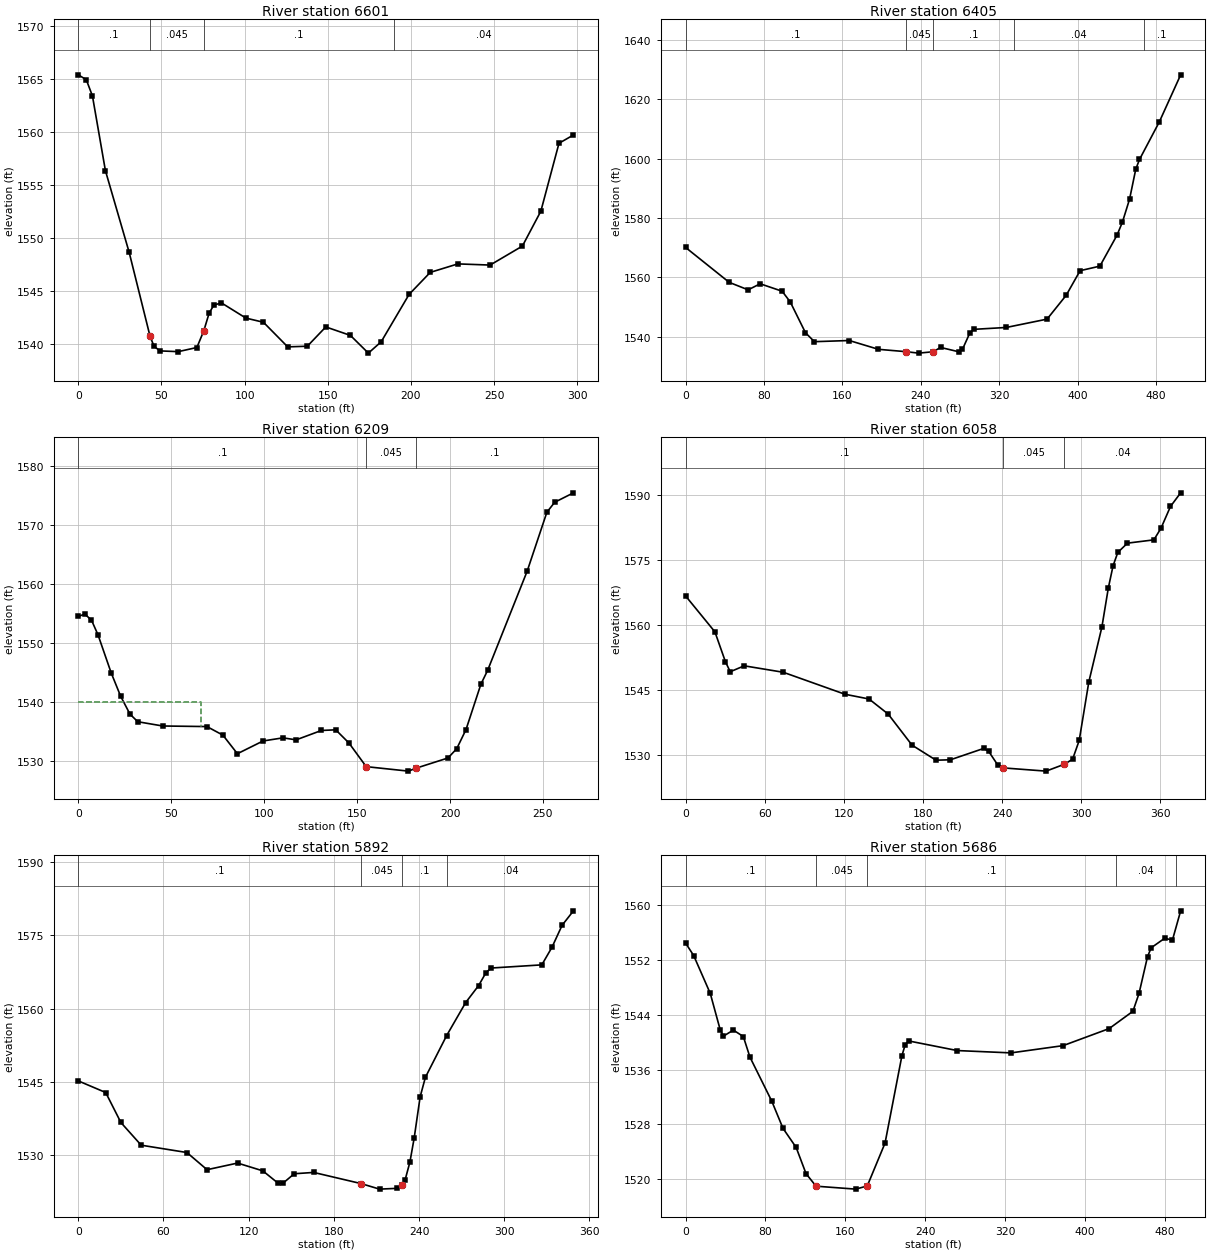
Type RM Length L Ch R = 1 ,6601    ,214.4,195.8,183.1
XS GIS Cut Line= 2
1997399.48863004302737.8034891271997135.02568209 302874.45400979
#Sta/Elev= 30
       0  1565.4     4.8 1564.94     8.5 1563.41    16.3 1556.37    30.6 1548.66
    43.1 1540.78    45.5 1539.82    49.1 1539.38    60.1 1539.31    71.3  1539.7
    75.51541.297    78.7 1542.96    81.5 1543.69      86 1543.91   100.8 1542.47
   111.3 1542.08   125.9 1539.76   137.7 1539.82   148.8 1541.64   163.6 1540.84
   174.4 1539.17   182.1 1540.24   198.9 1544.71   211.6 1546.78   228.2 1547.58
   247.6 1547.47     267 1549.26   278.1 1552.55     289 1558.95   297.7 1559.73
#Mann= 4 ,-1 , 0
       0      .1       0    43.1    .045       0    75.5      .1       0
     190     .04       0
Bank Sta=43.1,75.5
XS Rating Curve= 0 ,0
Exp/Cntr=0.3,0.1

Type RM Length L Ch R = 1 ,6405    ,178.5,196.2,210.5
XS GIS Cut Line= 4
1997334.76255046302501.5576784951997244.96554444302556.973712292
1997111.41720991302805.2944974681996996.77796364  302831.9135704
#Sta/Elev= 30
       0 1570.11    44.6 1558.32    63.9  1555.8    76.2 1557.84    98.6 1555.33
   106.9 1551.71   122.4 1541.35   131.5 1538.33   167.1 1538.72   196.9 1535.75
   224.7 1534.97   237.8 1534.47   252.7 1534.93   260.2 1536.39   278.8 1534.93
   282.6 1535.77     290 1541.18   293.9 1542.48   327.3 1543.12   368.9 1545.93
   388.4 1553.96   402.6 1562.25   422.8 1563.79   440.3 1574.24   445.8 1578.64
   453.1  1586.4   459.4 1596.46   463.2 1599.73   483.4 1612.38   505.2 1628.26
#Mann= 5 ,-1 , 0
       0      .1       0   224.7    .045       0   252.7      .1       0
  335.52     .04       0  467.47      .1       0
Bank Sta=224.7,252.7
XS Rating Curve= 0 ,0
Exp/Cntr(USF)=0,0
Exp/Cntr=0.3,0.1

Type RM Length L Ch R = 1 ,6209    ,153.2,151.3,156.5
XS GIS Cut Line= 2
1997201.65130908302486.2577545741996955.54440122302588.235755069
#Sta/Elev= 30
       0 1554.52     3.5 1554.93     7.1 1553.89    10.6 1551.41    17.7 1544.95
    22.8 1540.99    27.8 1537.97      32 1536.68    45.4 1535.96    69.2 1535.86
    77.8 1534.41    85.6 1531.26    99.4 1533.42   110.1 1533.95   117.2 1533.61
   130.8  1535.2   138.5 1535.31   145.6 1533.08   154.9 1529.07   177.6 1528.31
   181.71528.807   198.9 1530.54   203.6 1532.11   208.6 1535.36   216.6 1543.04
   220.2 1545.37   241.5  1562.2   252.1 1572.18   256.3 1573.87   266.4 1575.47
#Mann= 3 ,-1 , 0
       0      .1       0   154.9    .045       0   181.7      .1       0
#XS Ineff= 2 , 0
           66.27    1540
Permanent Ineff=
       F       F
Bank Sta=154.9,181.7
XS Rating Curve= 0 ,0
Exp/Cntr(USF)=0,0
Exp/Cntr=0.3,0.1

Type RM Length L Ch R = 1 ,6058    ,164.5,165.3,167.1
XS GIS Cut Line= 2
1997186.35908196302320.1227100231996846.95500577302480.303312853
#Sta/Elev= 30
       0 1566.67    22.3 1558.35    30.2  1551.5    33.9 1549.14    44.5 1550.51
    74.1 1549.02   120.9 1543.94   139.1 1542.85   153.6 1539.37   171.7 1532.19
   189.9 1528.71   200.8 1528.81   226.1 1531.44   229.8 1530.75   236.7 1527.59
   240.81526.936   273.3 1526.19   287.21527.783   293.4 1528.94   298.4 1533.27
   305.7  1546.8   315.6 1559.47   320.5 1568.52   324.1 1573.65   327.7 1576.71
     335 1578.84     355  1579.6   360.4 1582.29   367.6 1587.32   375.3 1590.46
#Mann= 3 ,-1 , 0
       0      .1       0   240.8    .045       0   287.2     .04       0
Bank Sta=240.8,287.2
XS Rating Curve= 0 ,0
Exp/Cntr(USF)=0,0
Exp/Cntr=0.3,0.1

Type RM Length L Ch R = 1 ,5892    ,199.5,206.9,222
XS GIS Cut Line= 2
1997081.58111295302196.0318943861996761.26861295302334.052727714
#Sta/Elev= 30
       0 1545.17    19.3 1542.79      30 1536.65    44.3    1532    76.5  1530.5
    90.7 1526.98   112.2 1528.34     130 1526.74   140.8  1524.2   144.3 1524.24
   152.1 1526.15   165.8 1526.42   199.31524.127   212.2    1523   224.5 1523.16
   228.3 1523.92   230.1 1524.77   233.6 1528.55   236.6 1533.47   240.8 1541.91
   244.5  1545.9   259.5 1554.47   272.9 1561.23     282  1564.7   287.2 1567.36
   290.8 1568.29   326.5 1568.94   333.7 1572.56   340.8 1577.05   348.8 1580.01
#Mann= 4 ,-1 , 0
       0      .1       0   199.3    .045       0   228.3      .1       0
     260     .04       0
Bank Sta=199.3,228.3
XS Rating Curve= 0 ,0
Exp/Cntr(USF)=0,0
Exp/Cntr=0.3,0.1

Type RM Length L Ch R = 1 ,5686    ,238.9,208.2,191.3
XS GIS Cut Line= 3
 1997091.7025869302102.7859901581996783.23621837302062.304960308
1996641.37991325302180.604898222
#Sta/Elev= 30
       0 1554.51     8.2 1552.66    24.8 1547.13    34.7 1541.84      38 1540.89
    47.9 1541.77    57.9 1540.83    64.5 1537.83    86.4 1531.38    97.6 1527.42
   110.8 1524.62   120.7 1520.79   130.7 1518.96   170.4 1518.53     1821518.994
   199.8 1525.26   216.7 1538.03     220 1539.65   223.3 1540.19   272.1 1538.78
   325.9 1538.44   378.1  1539.5   424.2 1541.99     448 1544.52   454.1 1547.12
   462.6 1552.49   466.3  1553.8   479.7 1555.18   487.6 1554.94   495.8  1559.2
#Mann= 5 ,-1 , 0
       0      .1       0   130.7    .045       0     182      .1       0
  431.11     .04       0  491.11      .1       0
Bank Sta=130.7,182
XS Rating Curve= 0 ,0
Exp/Cntr(USF)=0,0
Exp/Cntr=0.3,0.1

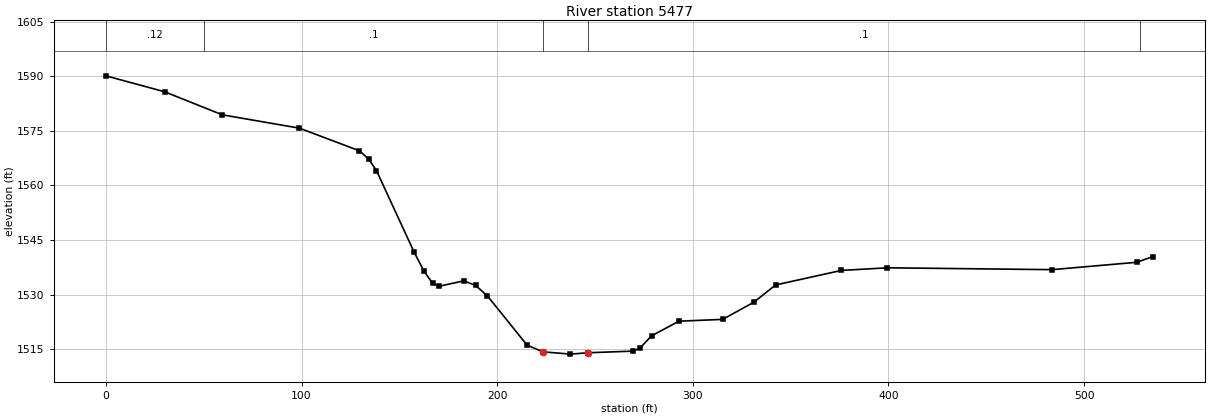
Type RM Length L Ch R = 1 ,5477    ,231.8,225.9,221
XS GIS Cut Line= 3
 1997080.6957995  301825.40573671996952.19428546301822.163190422
1996634.15339485302075.739066856
#Sta/Elev= 30
       0 1590.14      30 1585.76    59.5 1579.42    98.9 1575.76   129.6 1569.53
   134.3 1567.27   138.3  1564.1   157.6 1541.63   162.7 1536.36     167 1533.11
   170.3 1532.29   182.9 1533.78     189 1532.53     195 1529.66   215.3 1516.11
   223.41514.271   237.5 1513.64   246.41514.018   269.7 1514.47   273.2 1515.41
     279  1518.7     293  1522.7   315.3 1523.19   331.1 1527.87   342.4 1532.66
     376 1536.65   399.5 1537.37   483.7 1536.86     527 1538.89   535.3 1540.47
#Mann= 5 ,-1 , 0
       0     .12       0      50      .1       0   223.4    .045       0
   246.4      .1       0  528.54     .04       0
Bank Sta=223.4,246.4
XS Rating Curve= 0 ,0
Exp/Cntr=0.3,0.1