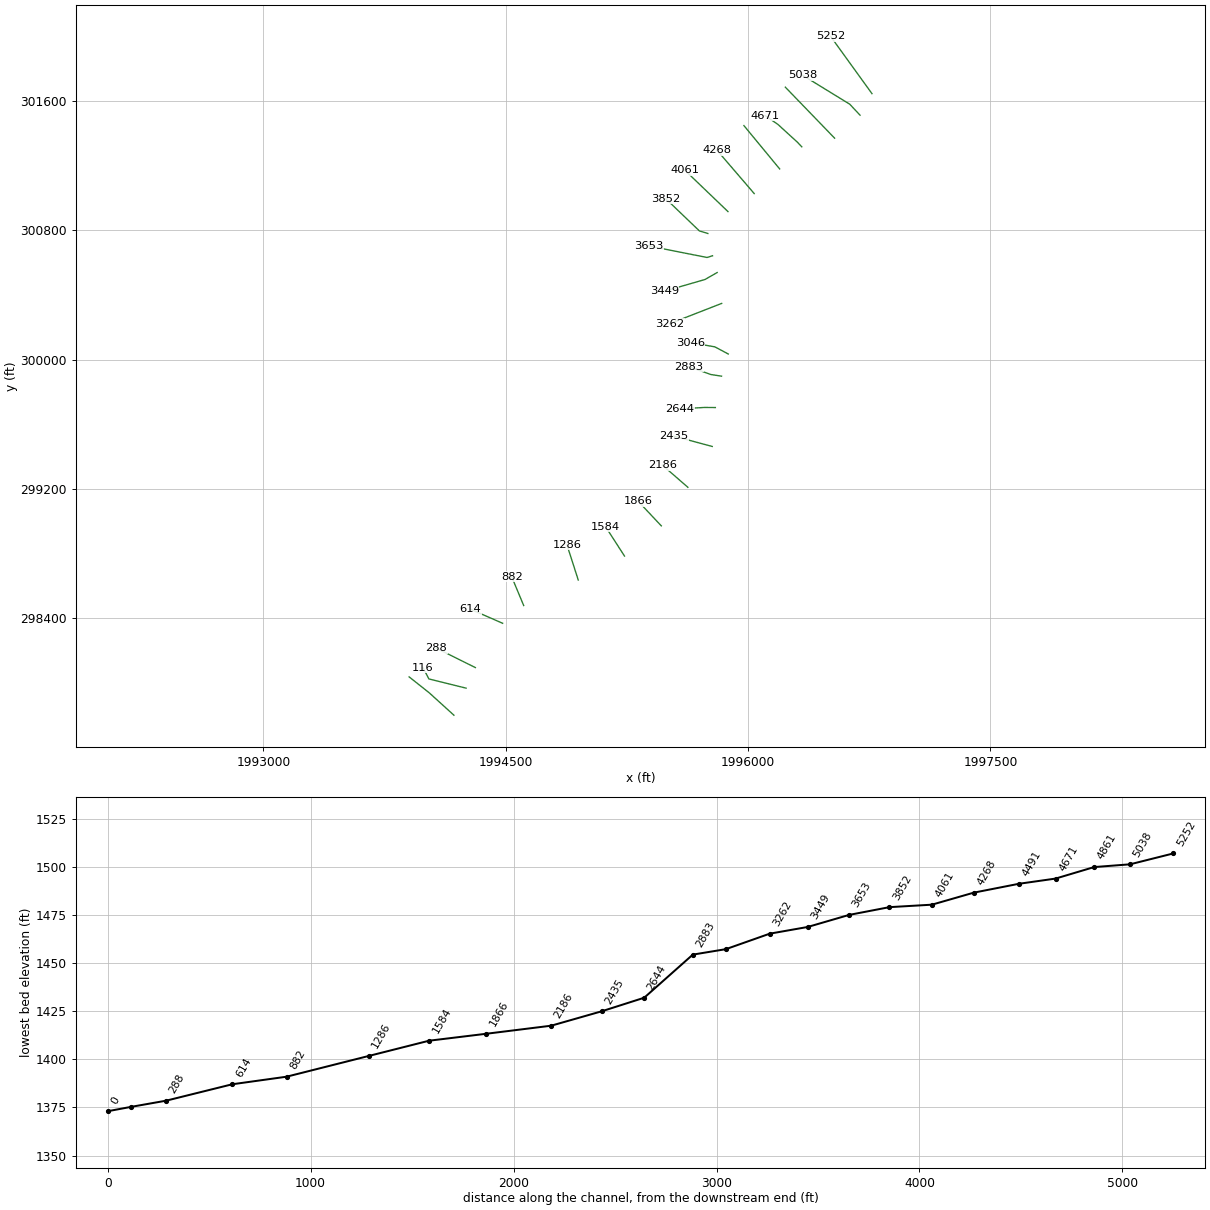
HEC-RAS study MEADOWCK_A.prj: MEADOWCK_A

--- MEADOWCK_A.g01 (geometry) --- (continued)

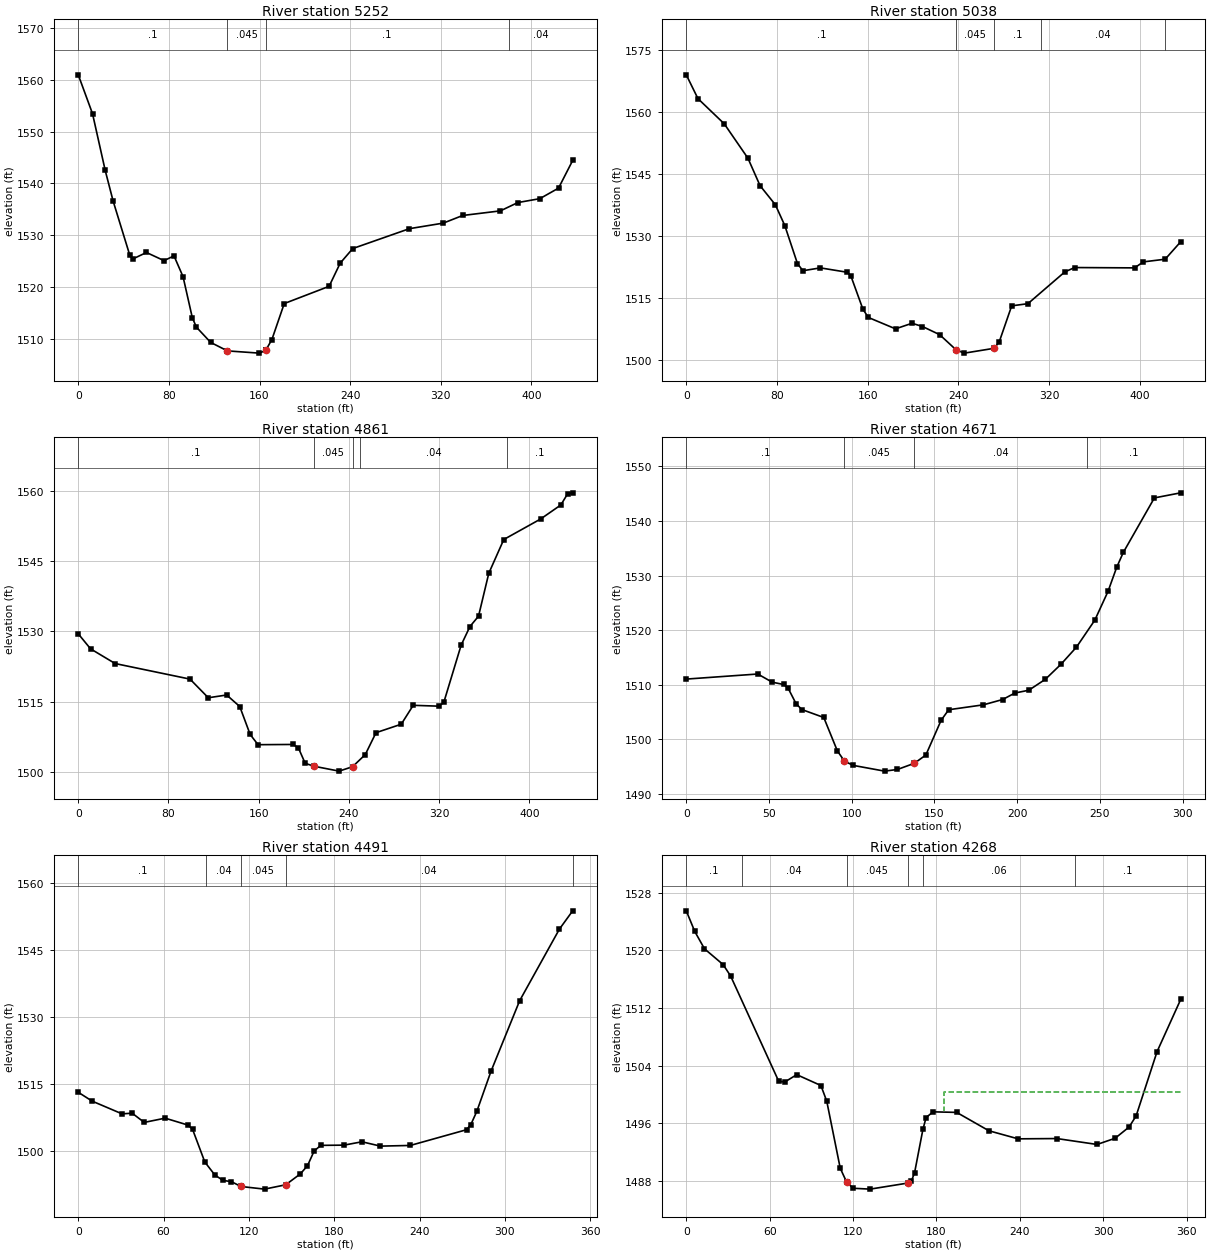
Type RM Length L Ch R = 1 ,5252    ,205,213.9,225.8
XS GIS Cut Line= 2
1996766.95630479301647.0174896881996511.41653899302000.835267595
#Sta/Elev= 30
       0 1560.92    12.6 1553.42    23.8 1542.49    30.8 1536.58    45.5 1526.15
    48.1 1525.44    60.2 1526.69    75.7 1525.12    84.5 1526.04    92.5 1522.02
   100.7  1514.1   104.3  1512.3   116.9 1509.36   131.7 1507.73   159.7  1507.3
   165.4 1507.81   165.4 1507.82   170.9 1509.91   181.8 1516.85   221.4 1520.17
   231.2 1524.64   242.3 1527.45   292.3 1531.28   322.2 1532.35   339.3 1533.82
   372.6 1534.71     388 1536.31   407.4 1537.06   423.9 1539.09   436.4 1544.42
#Mann= 4 ,-1 , 0
       0      .1       0   131.7    .045       0   165.4      .1       0
     380     .04       0
Bank Sta=131.7,165.4
XS Rating Curve= 0 ,0
Exp/Cntr=0.3,0.1

Type RM Length L Ch R = 1 ,5038    ,182.7,176.6,169.3
XS GIS Cut Line= 3
1996693.00934506301513.8006376731996629.74098053301581.407756035
1996336.99143282301761.209765929
#Sta/Elev= 30
       0    1569    10.3 1563.24    33.5 1557.14    54.4 1548.81    65.1 1542.16
    78.6 1537.54    86.9 1532.52    98.1 1523.29   102.9 1521.57   118.3 1522.26
     142  1521.2   145.3 1520.25   155.9 1512.21   160.7 1510.25   184.6  1507.5
   199.2 1508.85   208.4 1508.06   223.5  1506.1   238.21502.376   245.4 1501.62
   271.81502.796   276.2 1504.42   287.1 1513.07   301.4 1513.59   333.9 1521.27
   342.6 1522.34   395.5 1522.26   403.2 1523.71   422.5 1524.36   436.2 1528.58
#Mann= 5 ,-1 , 0
       0      .1       0   238.2    .045       0   271.8      .1       0
  312.59     .04       0  422.59      .1       0
Bank Sta=238.2,271.8
XS Rating Curve= 0 ,0
Exp/Cntr(USF)=0,0
Exp/Cntr=0.3,0.1

Type RM Length L Ch R = 1 ,4861    ,187.7,190.5,191.2
XS GIS Cut Line= 2
1996535.37545541301371.7449894941996230.69312529301687.009762862
#Sta/Elev= 30
       0 1529.48    10.9 1526.28    32.7 1523.14    99.1 1519.82   115.3 1515.84
   131.6 1516.43   143.2 1513.97   152.4 1508.02   159.4 1505.83   190.6 1505.88
   195.2 1505.14   201.2 1501.86     2091501.234   231.3 1500.19   243.21501.131
   254.5 1503.72     264 1508.39   286.4  1510.2     297 1514.23   319.5 1514.05
   324.1 1514.84   339.5 1527.07   347.3 1531.04   354.9 1533.24     364 1542.39
   377.3  1549.6     410 1553.98   427.9 1556.97   433.9 1559.35   438.4 1559.56
#Mann= 5 ,-1 , 0
       0      .1       0     209    .045       0   243.2      .1       0
     250     .04       0     380      .1       0
Bank Sta=209,243.2
XS Rating Curve= 0 ,0
Exp/Cntr=0.3,0.1

Type RM Length L Ch R = 1 ,4671    ,184.3,180,175.7
XS GIS Cut Line= 4
1996332.51057659301317.6831272511996305.09491619301346.717487875
1996185.16239114  301456.1717699 1996105.8927977301511.194193578
#Sta/Elev= 30
       0 1511.04    43.2 1511.97    51.9 1510.48    58.8 1510.05    61.4 1509.46
    66.3 1506.56    69.8 1505.47    83.1 1504.01    91.3  1497.9    95.61496.012
   100.9 1495.24   119.8 1494.19   127.6 1494.49   137.8 1495.62   144.8 1497.14
     154 1503.49   158.6 1505.43   179.6 1506.33   191.2  1507.3   198.6 1508.49
     207    1509     217    1511   226.4 1513.74   235.8 1516.89   246.9 1521.83
   254.9 1527.11   260.1 1531.49   264.1 1534.22   282.9 1544.21   298.8 1545.14
#Mann= 4 ,-1 , 0
       0      .1       0    95.6    .045       0   137.8     .04       0
   242.3      .1       0
Bank Sta=95.6,137.8
XS Rating Curve= 0 ,0
Exp/Cntr=0.3,0.1

Type RM Length L Ch R = 1 ,4491    ,221.9,222.7,222.3
XS GIS Cut Line= 2
1996195.42080912 301181.059651511995974.16210698 301449.22348788
#Sta/Elev= 30
       0 1513.13     9.8 1511.15    30.8 1508.31    37.9 1508.46    46.4  1506.4
    61.1 1507.35    77.4 1505.78    80.4 1504.84      89 1497.55      96 1494.67
   101.7 1493.44   107.7 1493.16   114.4 1492.08     131 1491.49   145.9 1492.46
   156.2  1494.9   161.2 1496.72   165.9 1500.02   170.6 1501.27   186.9 1501.32
   199.5 1502.07   212.5  1501.1   233.5 1501.25   273.1 1504.77   276.1 1505.93
   280.3 1508.88   290.2 1517.78   310.4 1533.59   338.4 1549.61   347.7 1553.68
#Mann= 5 ,-1 , 0
       0      .1       0      90     .04       0   114.4    .045       0
   145.9     .04       0  347.66      .1       0
Bank Sta=114.4,145.9
XS Rating Curve= 0 ,0
Exp/Cntr=0.3,0.1

Type RM Length L Ch R = 1 ,4268    ,204.2,206.5,209.7
XS GIS Cut Line= 2
 1996037.8142057301028.5822570841995806.06721782301298.565166496
#Sta/Elev= 30
       0  1525.5     6.1 1522.64    13.1 1520.23    26.5 1518.04    31.9 1516.46
    66.5 1501.85    70.8 1501.73    79.5 1502.76    96.9 1501.25   101.1 1499.07
   110.8 1489.77   115.41487.843   120.1 1486.99   132.3 1486.87   159.7 1487.72
     162    1488   164.3 1489.15   170.3 1495.17   172.6 1496.81   177.6  1497.6
   194.6 1497.52   217.8 1494.97   238.8 1493.85   266.7 1493.89   295.6 1493.07
   308.6 1493.93   318.6 1495.48   323.7 1497.02   338.8 1505.96   355.8  1513.2
#Mann= 6 ,-1 , 0
       0      .1       0      40     .04       0   115.4    .045       0
   159.7     .04       0     170     .06       0     280      .1       0
#XS Ineff= 2 , 0
                          185.42         1500.37
Permanent Ineff=
       F       F
Bank Sta=115.4,159.7
XS Rating Curve= 0 ,0
Exp/Cntr=0.3,0.1

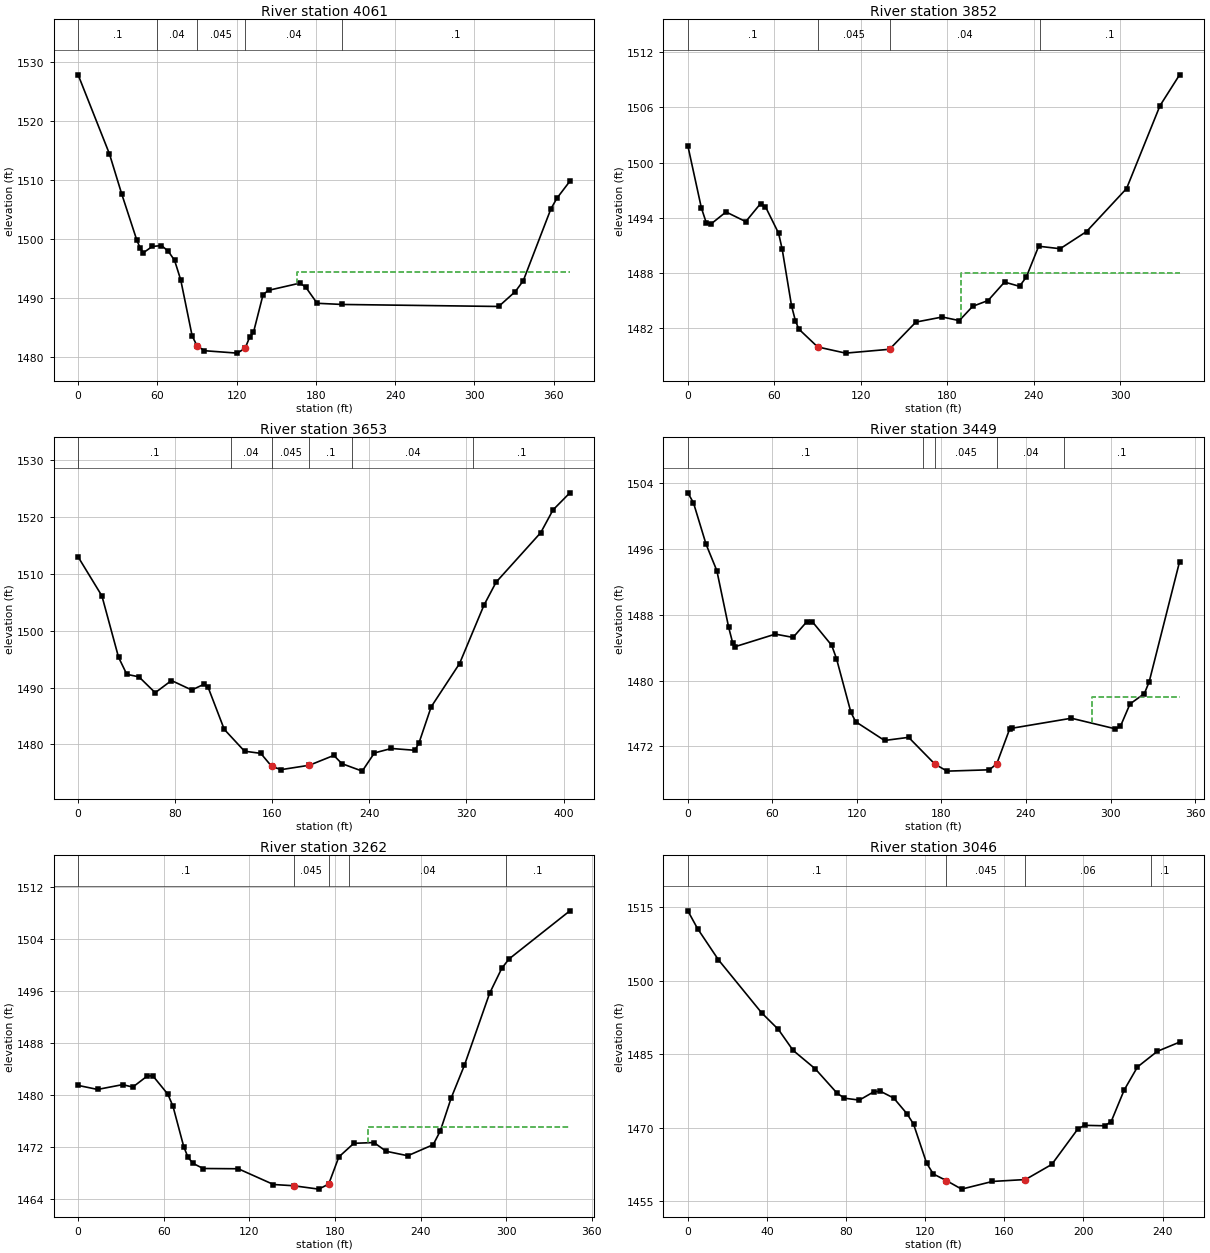
Type RM Length L Ch R = 1 ,4061    ,209.1,208.9,208.9
XS GIS Cut Line= 2
1995875.54980208300916.9773472841995606.95425446301174.567386751
#Sta/Elev= 30
       0 1527.84    23.7 1514.42    32.9 1507.68    44.5 1499.72    46.9 1498.48
    49.3 1497.63    56.1  1498.7    63.1 1498.86    68.2  1497.9      73 1496.35
    77.7 1492.99    86.3 1483.52      90 1481.84    95.6 1481.01   120.4  1480.6
   126.4 1481.43   129.8  1483.3   132.7 1484.11     140 1490.55   144.1 1491.26
   167.8 1492.48   172.2 1491.82   180.9 1489.06     200 1488.86   318.3 1488.52
   330.9 1491.05   336.9 1492.88   357.8 1505.07   362.4  1506.9   372.2 1509.78
#Mann= 5 ,-1 , 0
       0      .1       0      60     .04       0      90    .045       0
   126.4     .04       0     200      .1       0
#XS Ineff= 2 , 0
                          165.83         1494.29
Permanent Ineff=
       F       F
Bank Sta=90,126.4
XS Rating Curve= 0 ,0
Exp/Cntr=0.3,0.1

Type RM Length L Ch R = 1 ,3852    ,182.7,199.2,219.6
XS GIS Cut Line= 3
1995750.68909458300781.4826406821995698.79655219300797.117655828
1995491.52746076300995.761447619
#Sta/Elev= 30
       0 1501.83     9.4 1495.08    12.8 1493.47    16.3 1493.36    26.5 1494.64
    40.2 1493.59    50.5 1495.55    53.9  1495.2      63 1492.33    65.5 1490.59
      72 1484.44    74.7 1482.81    77.1 1481.92    90.11479.992   109.5 1479.32
     1401479.738   158.3 1482.69   176.6 1483.24   188.4 1482.85   197.7  1484.4
   208.4 1485.03   219.8 1487.03   230.2 1486.57   234.9 1487.57   243.5 1490.92
   258.4 1490.65   276.7 1492.51   304.5 1497.18   327.7 1506.17   341.3 1509.52
#Mann= 4 ,-1 , 0
       0      .1       0    90.1    .045       0     140     .04       0
   244.2      .1       0
#XS Ineff= 2 , 0
                           189.8            1488
Permanent Ineff=
       F       F
Bank Sta=90.1,140
XS Rating Curve= 0 ,0
Exp/Cntr=0.3,0.1

Type RM Length L Ch R = 1 ,3653    ,187.9,203.6,215.2
XS GIS Cut Line= 3
1995780.06786654300643.4851081731995745.99953896300632.862152378
1995383.51740966300704.657598031
#Sta/Elev= 30
       0    1513    19.6 1506.13    33.3 1495.33    40.1 1492.32    50.1 1491.88
    63.5 1489.08    76.9 1491.23    93.6 1489.56   103.8 1490.58     107 1490.09
   120.4 1482.63   137.1 1478.78   150.5  1478.4   159.4 1476.12   167.2 1475.53
   190.6 1476.31   210.7 1478.04   217.3 1476.59   234.1 1475.27   244.1 1478.47
   258.1 1479.26   277.5 1478.94   280.9 1480.26   290.9 1486.59   314.3 1494.22
   334.4  1504.5   344.4 1508.55   381.2 1517.28   391.3 1521.28   405.2 1524.29
#Mann= 6 ,-1 , 0
       0      .1       0  125.69     .04       0   159.4    .045       0
   190.6      .1       0  225.69     .04       0  325.69      .1       0
Bank Sta=159.4,190.6
XS Rating Curve= 0 ,0
Exp/Cntr=0.3,0.1

Type RM Length L Ch R = 1 ,3449    ,184.5,187.5,189.1
XS GIS Cut Line= 3
1995808.77538694300539.6881520421995733.14752457300496.611344172
1995481.50203326300423.883556347
#Sta/Elev= 30
       0 1502.78       4 1501.57      13 1496.51    20.6 1493.33      29 1486.44
    31.9 1484.52    33.8 1484.12    62.1 1485.63    74.7 1485.23    84.3 1487.11
    88.4 1487.13   102.1 1484.27   105.5 1482.66   115.7 1476.16   119.1    1475
   139.6 1472.72   156.7  1473.1   175.4 1469.84     184    1469   213.9 1469.16
   219.2 1469.87   228.4 1474.11   229.8  1474.2   272.2 1475.42   303.5 1474.13
     307 1474.43   313.8 1477.15     324 1478.41   327.4 1479.83     349 1494.43
#Mann= 5 ,-1 , 0
       0      .1       0  167.04     .04       0   175.4    .045       0
   219.2     .04       0  267.04      .1       0
#XS Ineff= 2 , 0
                           286.5            1478
Permanent Ineff=
       F       F
Bank Sta=175.4,219.2
XS Rating Curve= 0 ,0
Exp/Cntr=0.3,0.1

Type RM Length L Ch R = 1 ,3262    ,228.5,216,197.6
XS GIS Cut Line= 2
1995836.39765797300348.5155945291995515.35659898300223.185161985
#Sta/Elev= 30
       0 1481.44    13.6 1480.82    31.2 1481.56    38.3 1481.18    48.6 1482.91
    52.4  1482.9    62.9 1480.08    66.5 1478.21      74 1472.03      77 1470.39
    80.5 1469.46    87.6 1468.67   112.2 1468.63   136.9 1466.21     151 1466.02
   168.6  1465.5   175.6 1466.28   182.7 1470.45   193.2 1472.54   207.3 1472.66
   215.8 1471.32     231 1470.63   248.8 1472.33   253.8 1474.45   261.4  1479.5
   270.7 1484.54   288.3 1495.57   296.9 1499.45     302 1500.88   344.6 1508.27
#Mann= 5 ,-1 , 0
       0      .1       0     151    .045       0   175.6      .1       0
     190     .04       0     300      .1       0
#XS Ineff= 2 , 0
                           203.3            1475
Permanent Ineff=
       F       F
Bank Sta=151,175.6
XS Rating Curve= 0 ,0
Exp/Cntr(USF)=0,0
Exp/Cntr=0.3,0.1

Type RM Length L Ch R = 1 ,3046    ,166.4,162.8,156
XS GIS Cut Line= 3
1995877.24471723300035.4730172561995794.30261016300079.663484137
1995642.01546276300106.177764265
#Sta/Elev= 30
       0 1514.29     4.9 1510.67    15.5 1504.27    37.3 1493.46    45.8 1490.05
    53.2 1485.79    64.4 1482.02    75.5 1477.02    79.2 1476.01    86.7 1475.63
    94.1 1477.34    97.4 1477.42   104.1 1476.04   110.8 1472.83   114.1 1470.73
   120.7 1462.76   124.1 1460.53   130.7 1459.19   138.4 1457.44     154 1459.01
   170.7  1459.4     184 1462.49   197.3  1469.8   200.7 1470.47   210.7 1470.38
     214 1471.22   220.6 1477.69   227.3 1482.39   237.3 1485.58   248.6 1487.47
#Mann= 4 ,-1 , 0
       0      .1       0   130.7    .045       0   170.7     .06       0
  233.98      .1       0
Bank Sta=130.7,170.7
XS Rating Curve= 0 ,0
Exp/Cntr(USF)=0,0
Exp/Cntr=0.3,0.1

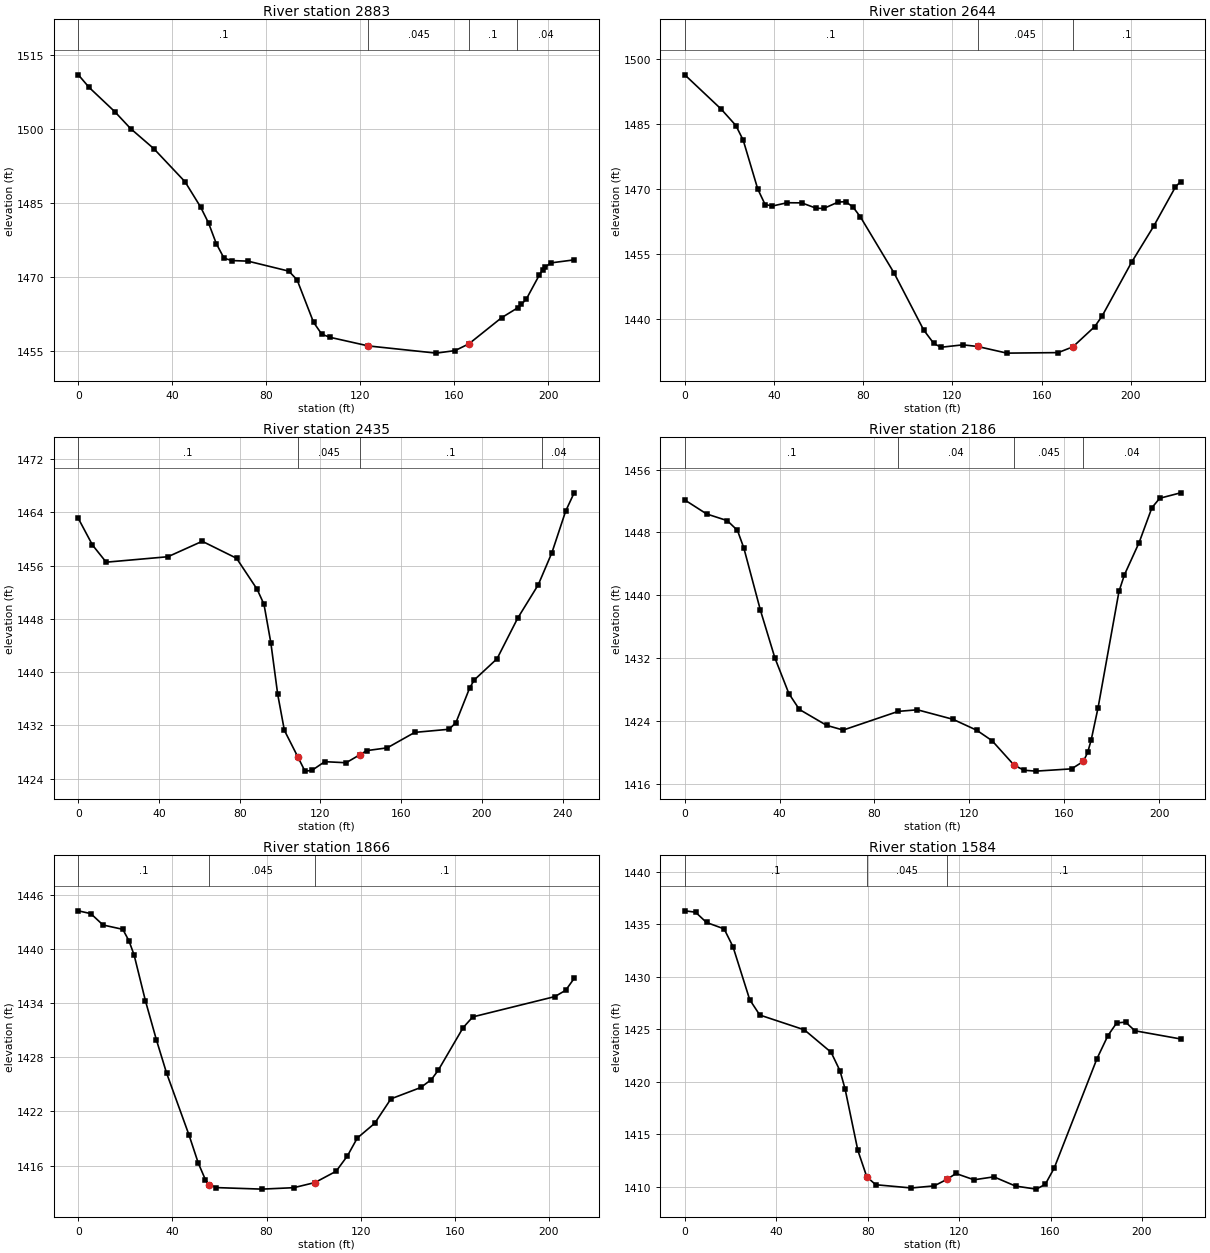
Type RM Length L Ch R = 1 ,2883    ,232.7,239.5,256.9
XS GIS Cut Line= 3
 1995835.7736637299898.1426432561995769.82789005299908.340443306
1995633.85722272299956.610030207
#Sta/Elev= 30
       0 1511.06     4.6  1508.5    15.5 1503.59    22.2 1500.17    32.1 1496.09
    45.4 1489.37      52 1484.27    55.4 1481.01    58.7 1476.83      62 1473.86
    65.3 1473.38    72.2 1473.26    89.6 1471.23    93.1 1469.46   100.1 1460.85
   103.6 1458.44     107 1457.82   123.41456.062   152.3  1454.6   160.3 1455.11
   166.2 1456.48   180.1 1461.78   187.1 1463.83   188.5 1464.48   190.6 1465.52
   196.2 1470.46   197.6 1471.53   198.8 1472.09     201  1472.9     211 1473.52
#Mann= 4 ,-1 , 0
       0      .1       0   123.4    .045       0   166.2      .1       0
  186.73     .04       0
Bank Sta=123.4,166.2
XS Rating Curve= 0 ,0
Exp/Cntr(USF)=0,0
Exp/Cntr=0.3,0.1

Type RM Length L Ch R = 1 ,2644    ,213.6,208.5,197.4
XS GIS Cut Line= 3
  1995797.403252299704.0415866541995727.67698317299704.384442317
1995575.38983577299695.546348941
#Sta/Elev= 30
       0 1496.29    16.3 1488.39    22.9 1484.61    26.2 1481.21    32.7 1469.98
      36  1466.4    39.3 1466.06    45.9 1466.81    52.4 1466.78      59 1465.53
    62.3  1465.5    68.8 1466.97    72.1 1467.05    75.4 1465.83    78.7 1463.57
    93.8 1450.64   107.1 1437.48   111.6  1434.4   114.8  1433.5   124.7 1434.06
   131.3 1433.68   144.4 1432.15   167.4 1432.27     174  1433.6   183.8 1438.27
   187.1  1440.7   200.3 1453.08   210.2 1461.38     220 1470.47   222.3 1471.69
#Mann= 3 ,-1 , 0
       0      .1       0   131.3    .045       0     174      .1       0
Bank Sta=131.3,174
XS Rating Curve= 0 ,0
Exp/Cntr=0.3,0.1

Type RM Length L Ch R = 1 ,2435    ,256,249.7,232.4
XS GIS Cut Line= 2
1995777.98613009299463.036507813 1995540.7173156299526.942721457
#Sta/Elev= 30
       0 1463.08       7 1459.09    13.8 1456.51    44.4 1457.33    61.4 1459.65
    78.4  1457.1    88.6 1452.44      92 1450.18    95.4 1444.39    98.8 1436.65
   102.1 1431.25   108.9 1427.18   112.3 1425.12   115.7 1425.22   122.1 1426.54
   132.7 1426.38   139.5 1427.58   142.9  1428.2   153.1 1428.62   166.7 1430.94
   183.7 1431.41   187.1  1432.4   193.9  1437.6   196.2 1438.82   207.5 1442.01
   217.7 1448.09   227.9 1453.11   234.7 1457.96   241.5 1464.19   245.7 1466.93
#Mann= 4 ,-1 , 0
       0      .1       0   108.9    .045       0   139.5      .1       0
     230     .04       0
Bank Sta=108.9,139.5
XS Rating Curve= 0 ,0
Exp/Cntr(USF)=0,0
Exp/Cntr=0.3,0.1

Type RM Length L Ch R = 1 ,2186    ,319.9,319.2,305.7
XS GIS Cut Line= 2
1995627.21805575299210.2782269991995469.35611098299347.336659663
#Sta/Elev= 30
       0 1452.12     9.2 1450.34    17.9 1449.49    22.2 1448.25    24.9    1446
    31.9 1438.07      38    1432    43.9 1427.46    48.3 1425.45    59.8 1423.42
    66.8 1422.82      90  1425.2    98.1  1425.4   113.1 1424.19   123.1  1422.8
   129.6 1421.46   138.9 1418.34   143.1  1417.7   148.1 1417.59   163.1 1417.88
   168.1 1418.83   169.9 1419.98   171.4 1421.58   174.3 1425.69   183.1 1440.47
   185.4 1442.59   191.6  1446.7     197 1451.14   200.3 1452.34   209.1 1453.03
#Mann= 4 ,-1 , 0
       0      .1       0      90     .04       0   138.9    .045       0
   168.1     .04       0
Bank Sta=138.9,168.1
XS Rating Curve= 0 ,0
Exp/Cntr(USF)=0,0
Exp/Cntr=0.3,0.1

Type RM Length L Ch R = 1 ,1866    ,286.7,282.7,275.2
XS GIS Cut Line= 2
1995462.62556295298971.6497058421995318.22471425299125.228574586
#Sta/Elev= 30
       0 1444.23     5.3 1443.92    10.5 1442.66    18.9 1442.18    21.5 1440.92
    23.7 1439.35    28.5 1434.29    33.2 1429.93    37.5 1426.27    47.1 1419.36
      51 1416.28      54 1414.46    55.5 1413.89    58.7 1413.57      78  1413.4
    91.6 1413.56   100.6 1414.13   109.6 1415.38   114.4 1417.08   118.6 1419.06
     126 1420.69   132.9  1423.4   145.6 1424.66   150.1 1425.54     153 1426.56
   163.6 1431.29   167.7 1432.48   202.6 1434.73   207.2 1435.43   210.8 1436.74
#Mann= 3 ,-1 , 0
       0      .1       0    55.5    .045       0   100.6      .1       0
Bank Sta=55.5,100.6
XS Rating Curve= 0 ,0
Exp/Cntr(USF)=0,0
Exp/Cntr=0.3,0.1

Type RM Length L Ch R = 1 ,1584    ,305.4,297.2,291.9
XS GIS Cut Line= 2
1995235.01066585298784.4180969341995117.53200928298966.754761818
#Sta/Elev= 30
       0 1436.29     4.7 1436.16     9.5 1435.18    17.2 1434.57    21.1 1432.86
    28.4 1427.82    32.8 1426.36    52.3 1424.95      64 1422.81    67.9 1421.04
    70.1 1419.33    75.7 1413.46    79.6 1410.95    83.5 1410.19    99.1 1409.88
   109.1 1410.08   114.81410.715   118.6 1411.26   126.5 1410.66   135.2 1410.94
   144.7 1410.06   153.8 1409.77   157.7 1410.23   161.6 1411.78   180.3  1422.2
   185.1  1424.4   188.9  1425.6   192.8 1425.69   196.9 1424.86   216.9 1424.08
#Mann= 3 ,-1 , 0
       0      .1       0    79.6    .045       0   114.8      .1       0
Bank Sta=79.6,114.8
XS Rating Curve= 0 ,0
Exp/Cntr(USF)=0,0
Exp/Cntr=0.3,0.1

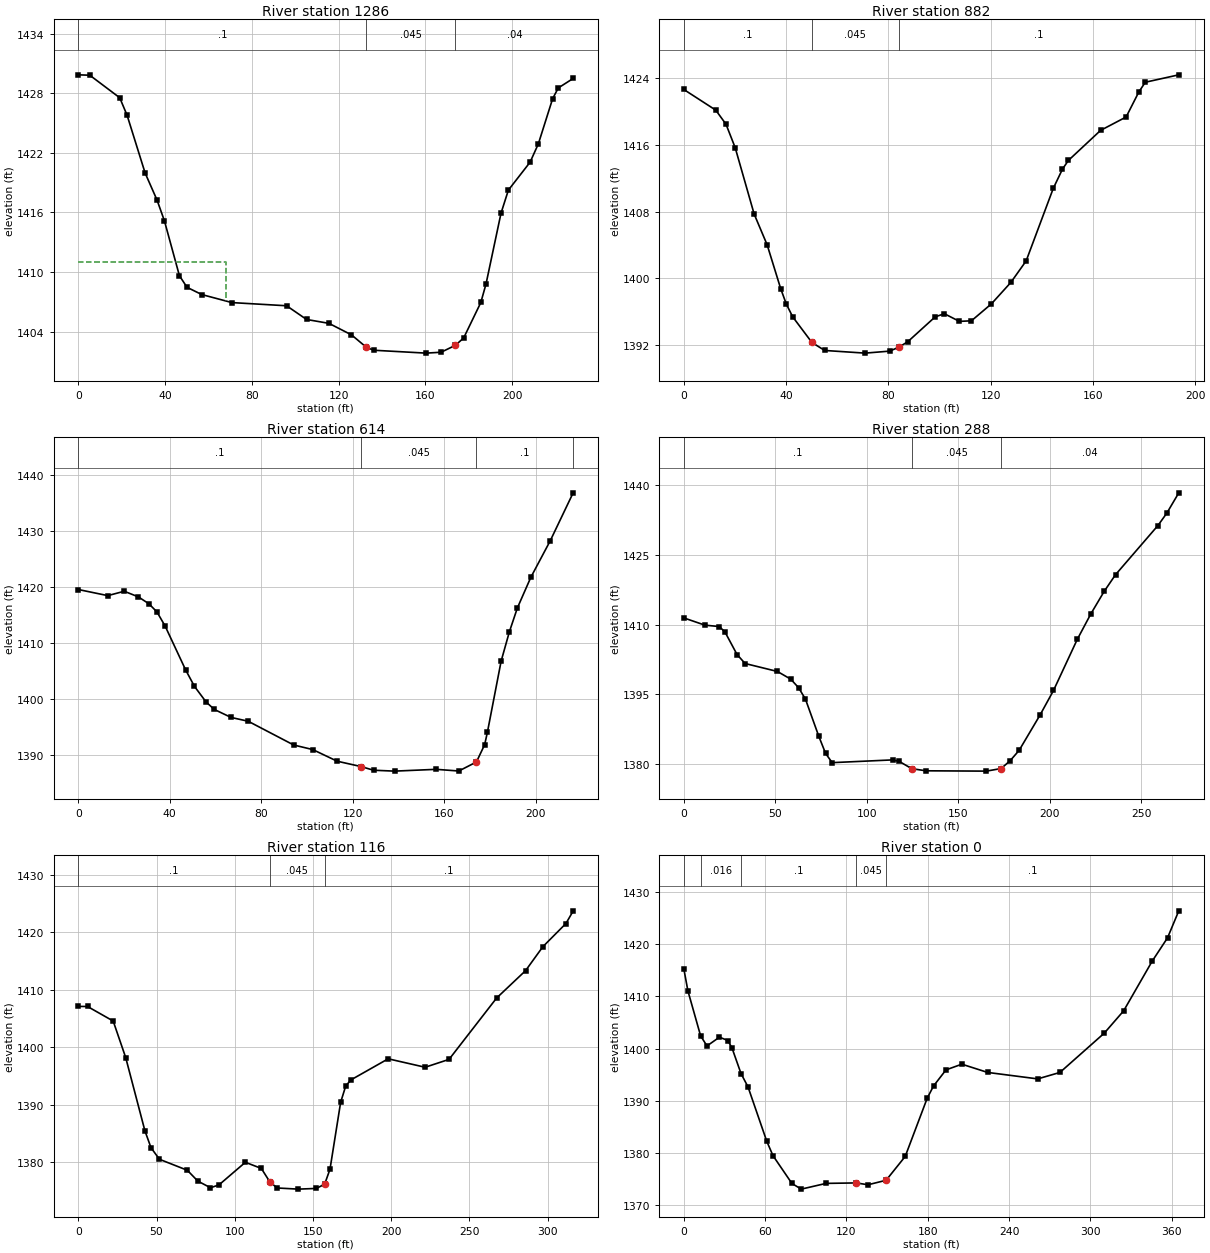
Type RM Length L Ch R = 1 ,1286    ,401.2,404.8,408.5
XS GIS Cut Line= 2
1994948.65644046298636.3460402161994878.90348812298853.559181269
#Sta/Elev= 30
       0 1429.86     5.3 1429.82    19.1 1427.55    22.5 1425.78    30.8 1419.97
    36.3 1417.24    39.7 1415.15    46.6 1409.63    50.1 1408.46    56.9 1407.73
    70.8 1406.92      96  1406.6   105.2 1405.22   115.5 1404.83   125.9 1403.67
   132.8 1402.41   136.2 1402.12   160.3 1401.83   167.2 1401.92   173.8 1402.62
   177.6 1403.36   185.5 1406.93   187.9  1408.8   194.8 1415.92   198.2 1418.25
   208.2 1421.06     212  1422.9   218.6 1427.46   221.2 1428.54   228.1  1429.5
#Mann= 3 ,-1 , 0
       0      .1       0   132.8    .045       0   173.8     .04       0
#XS Ineff= 2 , 0
              68    1411
Permanent Ineff=
       F       F
Bank Sta=132.8,173.8
XS Rating Curve= 0 ,0
Exp/Cntr(USF)=0,0
Exp/Cntr=0.3,0.1

Type RM Length L Ch R = 1 ,882     ,250,267.2,302.7
XS GIS Cut Line= 2
1994610.90530282 298478.484095451994536.25740646298657.149552317
#Sta/Elev= 30
       0 1422.67    12.5 1420.19    16.5  1418.5    20.1 1415.68    27.5 1407.73
    32.6 1404.02    37.9 1398.76    40.1 1396.91    42.6 1395.38    50.1 1392.31
    55.1 1391.35    70.9 1391.03    80.5 1391.27    84.1 1391.74    87.6  1392.4
    98.3 1395.38   101.9 1395.76   107.8 1394.84   112.5 1394.91   120.3 1396.94
   127.9 1399.51   133.9  1402.1   144.5  1410.8   148.1 1413.11   150.4 1414.15
     163 1417.76     173 1419.37     178 1422.39   180.5 1423.54   193.6 1424.43
#Mann= 3 ,-1 , 0
       0      .1       0    50.1    .045       0    84.1      .1       0
Bank Sta=50.1,84.1
XS Rating Curve= 0 ,0
Exp/Cntr(USF)=0,0
Exp/Cntr=0.3,0.1

Type RM Length L Ch R = 1 ,614     ,323,326,319
XS GIS Cut Line= 2
1994480.57741819298368.3478549161994282.33218523298455.233111338
#Sta/Elev= 30
       0  1419.5    12.9 1418.41    20.1 1419.19    26.3 1418.18    30.9 1416.95
    34.4  1415.5      38 1412.96    46.9 1405.19    50.8 1402.22    55.9 1399.43
    59.5  1398.1    66.8 1396.68    74.3    1396    94.2 1391.76   102.5 1390.95
   113.2 1388.87   123.7 1387.91   129.1 1387.26   138.3  1387.1   156.5 1387.42
   166.4 1387.12   174.1 1388.73   177.7 1391.82   178.9 1394.03   184.9 1406.71
   188.5 1411.94     192  1416.2   197.9 1421.68   206.4 1428.21   216.4 1436.75
#Mann= 4 ,-1 , 0
       0      .1       0   123.7    .045       0   174.1      .1       0
  216.45     .04       0
Bank Sta=123.7,174.1
XS Rating Curve= 0 ,0
Exp/Cntr(USF)=0,0
Exp/Cntr=0.3,0.1

Type RM Length L Ch R = 1 ,288     ,164.7,172.1,178.2
XS GIS Cut Line= 2
1994311.70184937298094.230989587 1994069.4021202298214.768986172
#Sta/Elev= 30
       0 1411.44    11.5 1409.89    19.4 1409.58    22.5 1408.42    29.1 1403.58
    33.5 1401.65    51.2 1399.94    58.5 1398.28    62.8 1396.43    66.5    1394
    73.8 1386.02    77.5 1382.36    81.1 1380.37   114.1 1380.96   117.8 1380.63
   124.6 1379.08   132.4 1378.62   165.4 1378.55   173.5 1379.11   178.4 1380.79
   183.3    1383   194.7 1390.56   202.1 1395.86   215.1 1406.83   222.5 1412.29
   229.8 1417.13     236 1420.71   259.2 1431.27   264.1 1433.96   270.6 1438.29
#Mann= 3 ,-1 , 0
       0      .1       0   124.6    .045       0   173.5     .04       0
Bank Sta=124.6,173.5
XS Rating Curve= 0 ,0
Exp/Cntr(USF)=0,0
Exp/Cntr=0.3,0.1

Type RM Length L Ch R = 1 ,116     ,127.9,116.3,105.1
XS GIS Cut Line= 3
1994254.18625709 297966.962444971994024.12388798298023.866169246
 1993987.4118078298094.230989587
#Sta/Elev= 30
       0 1407.12     5.9 1407.11    22.3 1404.58    30.3 1398.23    42.6 1385.47
    46.5 1382.53    51.9 1380.53    69.7 1378.62    76.4 1376.74    84.5 1375.58
    89.9 1376.07   106.8 1380.01     117 1378.94   122.4 1376.62   127.1 1375.54
   140.6 1375.34   152.2 1375.46   157.5 1376.21   160.9 1378.81   167.7 1390.44
     171 1393.32   174.4 1394.36   198.1 1398.01   221.7 1396.54     237 1397.91
   267.4 1408.58   285.9 1413.34     297 1417.52   311.7 1421.54   316.4 1423.75
#Mann= 3 ,-1 , 0
       0      .1       0   122.4    .045       0   157.5      .1       0
Bank Sta=122.4,157.5
XS Rating Curve= 0 ,0
Exp/Cntr(USF)=0,0
Exp/Cntr=0.3,0.1

Type RM Length L Ch R = 1 ,0       ,142.2,147.8,111.2
XS GIS Cut Line= 3
1994178.98589757297799.331470721 1994026.1354091297938.121066763
1993901.60060795298036.726212115
#Sta/Elev= 30
       0 1415.31       3 1411.09    12.4 1402.44    17.1 1400.51    26.3 1402.19
    32.5 1401.55    35.6 1400.09    42.2 1395.22    47.4 1392.64    61.2 1382.24
    65.8 1379.47    79.8 1374.13    86.7 1373.05     105 1374.15   127.1 1374.24
     136 1373.89   149.3 1374.75   163.4 1379.32   179.6 1390.47   184.3 1392.83
   193.5 1395.92   205.2 1397.01   224.2 1395.43   261.2 1394.19   277.6 1395.43
   310.3 1402.96   324.6 1407.24   345.7 1416.78     357 1421.24365.3057 1426.42
#Mann= 5 ,-1 , 0
       0      .1       0    12.4    .016       0    42.2      .1       0
   127.1    .045       0   149.3      .1       0
Bank Sta=127.1,149.3
XS Rating Curve= 0 ,0
Exp/Cntr(USF)=0,0
Exp/Cntr=0.3,0.1
LCMann Table=0

Chan Stop Cuts=-1
Use User Specified Reach Order=0
Composite Channel Slope=5